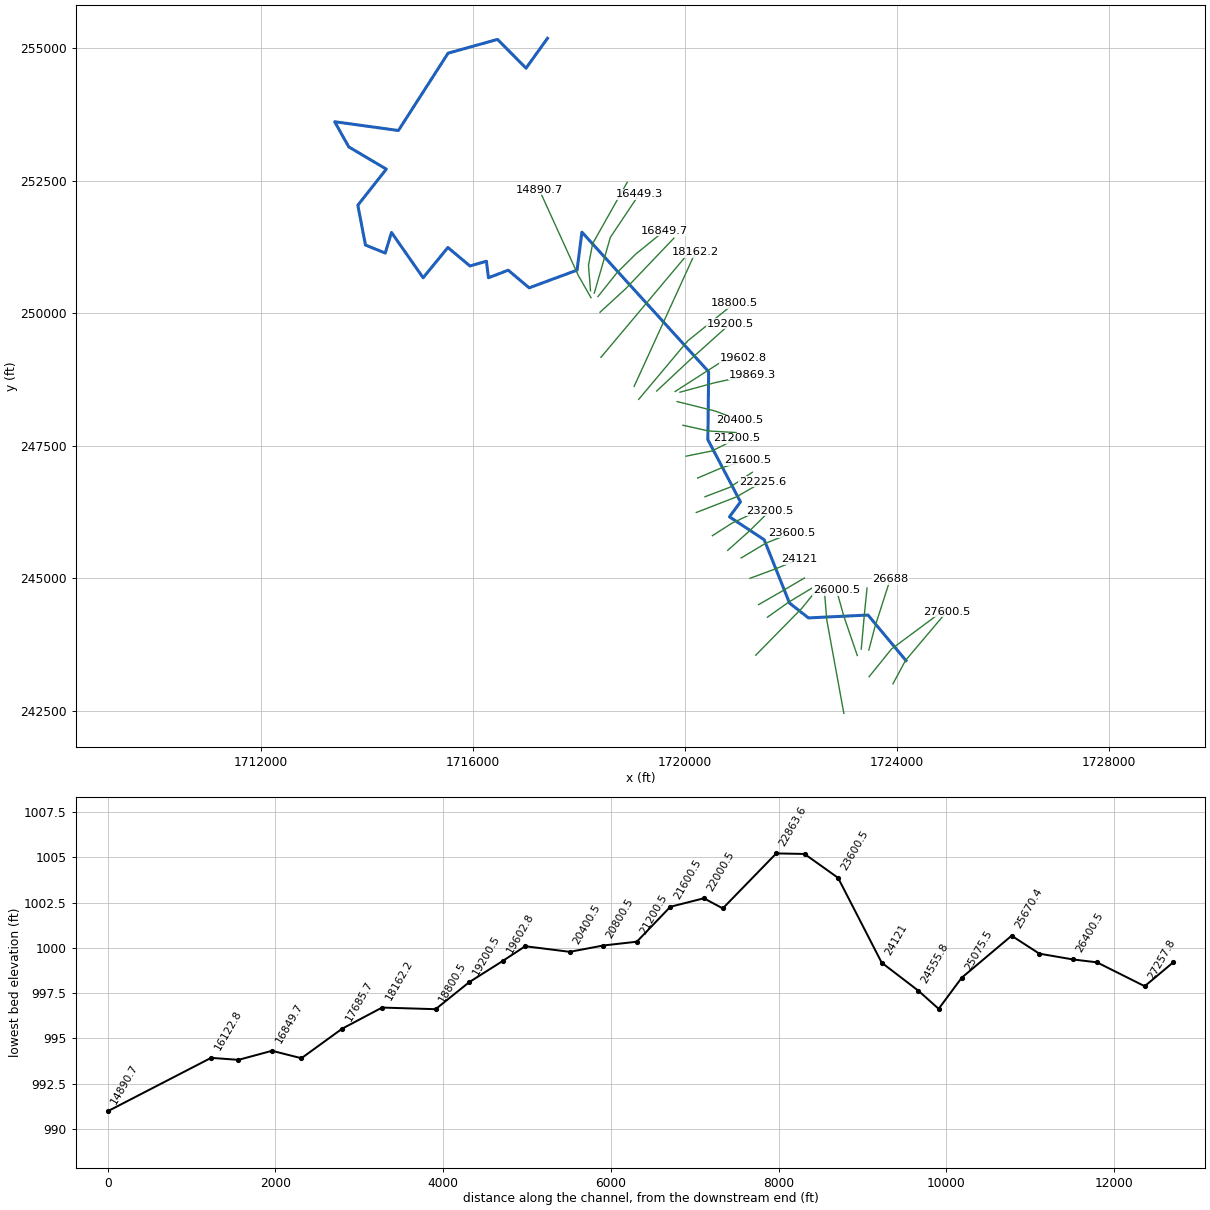
--- LostCrLR.prj (project) ---

Proj Title=LostCrLR
Current Plan=p01
Default Exp/Contr=0,0
English Units
Geom File=g01
Flow File=f01
Plan File=p01
BEGIN DESCRIPTION:
END DESCRIPTION:
DSS Export Rating Curves= 0
DSS Export Rating Curve Sorted= 0
DSS Export Volume Flow Curves= 0
DXF OffsetX= 0
DXF OffsetY= 0
DXF ScaleX= 0
DXF ScaleY= 0

--- LostCrLR.p01 (plan) ---

Plan Title=Floodplain
Program Version=4.00
Geom File=g01
Flow File=f01
K Sum by GR=0
Std Step Tol=0.01
Critical Tol=0.01
Num of Std Step Trials=20
Max Error Tol=0.3
Flow Tol Ratio=0.001
Split Flow NTrial=30
Split Flow Tol=0.02
Split Flow Ratio=0.02
Log Output Level=0
Friction Slope Method=1
Unsteady Friction Slope Method=2
Unsteady Bridges Friction Slope Method=1
Global Log Level=0
CheckData=False
Run HTab=0
Run UNet=0
Run PostProcess=0
UNET Theta=0
UNET Theta Warmup=0
UNET ZTol=0
UNET ZSATol=0
UNET MxIter=0
UNET MaxInSteps=0
UNET DtIC=0
UNET DtMin=0
UNET MaxCRTS=0
UNET WFStab=0
UNET SFStab=0
UNET WFX=0
UNET SFX=0
UNET DSS MLevel=0
UNET DZMax Abort=0
UNET Convert EG Bridges=0
UNET Use Existing IB Tables=0
UNET Froude Limit=0
UNET Froude Power=0
Write IC File=0
Echo Input=False
Echo Output=False
Write Detailed=0

--- LostCrLR.f01 (steady flow) ---

Flow Title=NFF Regression Equation
Program Version=4.00
Number of Profiles= 1
Profile Names=P100yr
River Rch & RM=LostCrLR,Main            ,27600.5
3244.379
River Rch & RM=LostCrLR,Main            ,24555.8
3524.856
River Rch & RM=LostCrLR,Main            ,18162.2
3752.042
River Rch & RM=LostCrLR,Main            ,12000.5
4168.797
River Rch & RM=LostCrLR,Main            ,8400.5
 4192.04
River Rch & RM=LostCrLR,Main            ,357.4
 4243.38
River Rch & RM=LostCrLR,Main            ,0.5
4245.936
Boundary for River Rch & Prof#=LostCrLR,Main            , 1
Up Type= 0
Dn Type= 3
Dn Slope=0.00277
DSS Import GetInterval= 0
DSS Import GetPeak= 0
DSS Import FillOption= 0

--- LostCrLR.g01 (geometry) ---

Geom Title=USGS 3m DEM
Program Version=4.00

River Reach=LostCrLR     ,Main
Reach XY= 30
     1724165.799      243443.649     1723448.579      244304.517
     1722325.811      244250.244     1721968.829      244529.420
     1721490.319      245725.231     1720835.144      246157.355
     1721043.354      246438.385     1720428.167      247611.570
     1720442.486      248894.191     1718051.741      251527.944
     1717960.335      250810.693     1717056.637      250476.840
     1716661.595      250809.747     1716288.921      250667.228
     1716250.297      250978.359     1715940.132      250889.483
     1715523.750      251237.763     1715056.636      250666.667
     1714459.799      251521.657     1714341.541      251132.600
     1713968.814      251284.511     1713824.629      252035.442
     1714362.223      252716.395     1713654.164      253135.501
     1713387.725      253610.528     1714590.243      253445.050
     1715527.406      254903.884     1716460.001      255163.241
     1716997.325      254620.939     1717402.136      255183.629

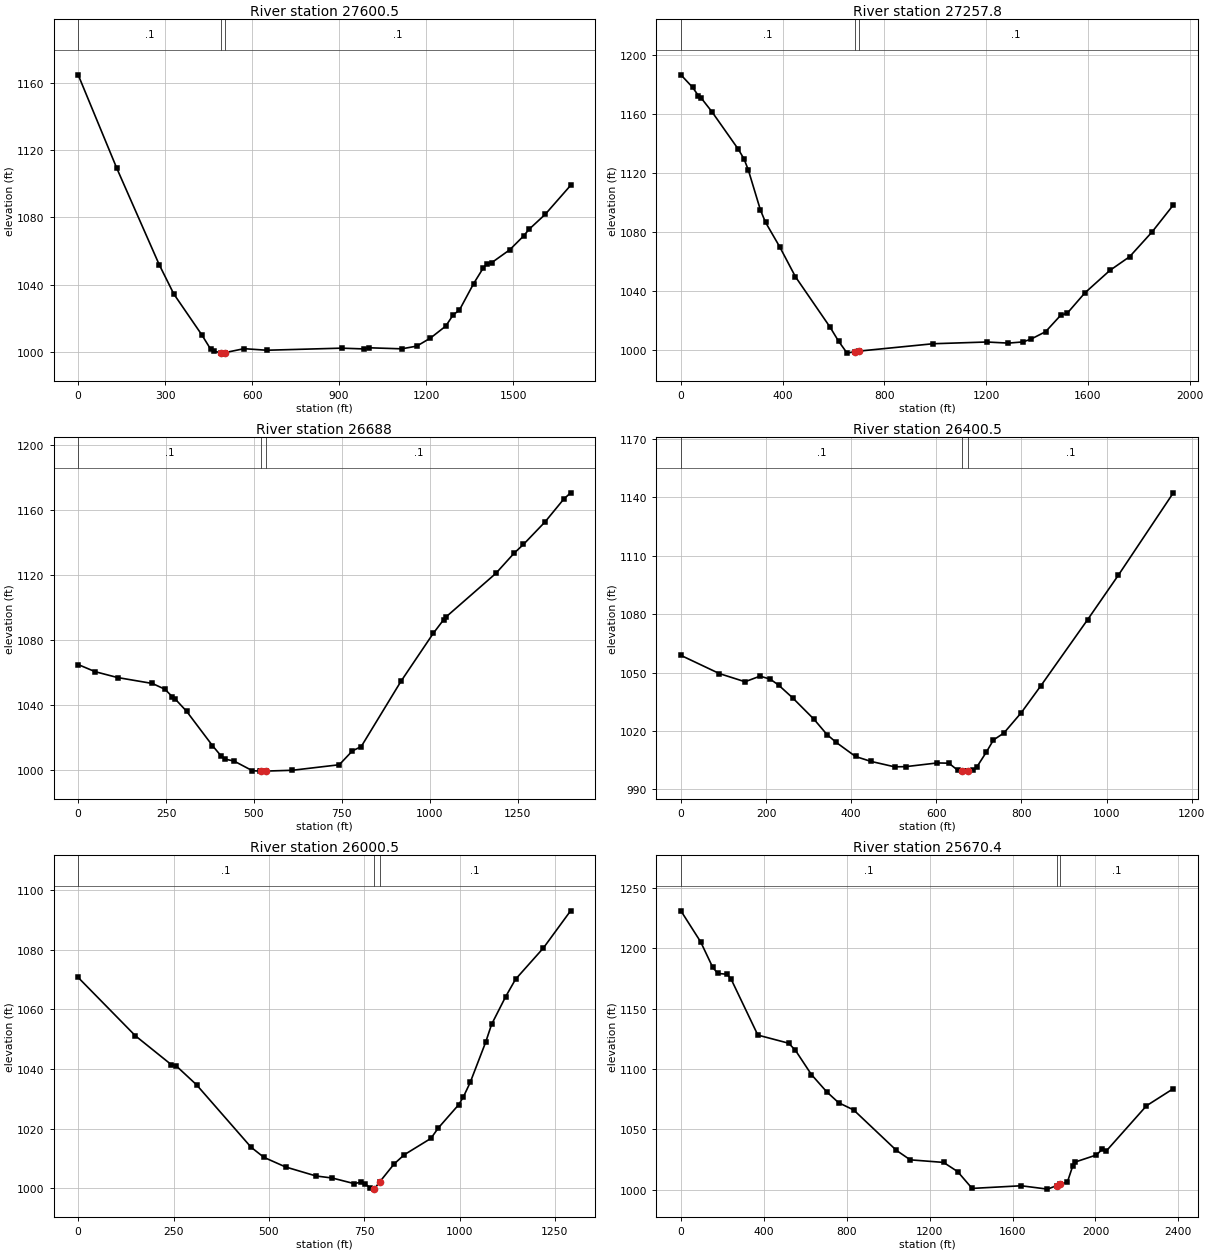
Type RM Length L Ch R = 1 ,27600.5,351.613,342.625,337.497
XS GIS Cut Line= 3
     1723919.859      243007.992     1724156.994      243448.390
     1724930.323      244363.662
#Sta/Elev= 30
       0 1164.90   133.1 1109.33   279.3 1051.97   329.8 1034.44   426.0 1010.21
   457.0 1001.55   467.9 1000.26   492.7  999.54   498.5  999.21   507.7  999.56
   572.3 1001.86   649.9 1000.93   908.8 1002.17   986.2 1001.71  1002.8 1002.39
  1116.1 1001.77  1168.0 1003.39  1215.2 1008.20  1267.9 1015.32  1293.9 1022.11
  1314.5 1024.70  1364.1 1040.65  1397.7 1050.06  1410.2 1052.39  1426.9 1053.15
  1488.3 1060.70  1536.2 1068.93  1554.7 1072.86  1610.5 1081.77  1698.4 1099.07
#Mann= 3 , 0 , 0
       0     0.1       0   492.7   0.045       0   507.7     0.1       0
Bank Sta=   492.7,   507.7
Exp/Cntr=0.3,0.1

Type RM Length L Ch R = 1 ,27257.8,555.302,569.811,584.988
XS GIS Cut Line= 3
     1723469.705      243141.355     1723892.515      243664.102
     1724907.261      244417.474
#Sta/Elev= 30
       0 1186.78    45.7 1178.34    68.4 1172.71    79.4 1171.12   121.8 1161.76
   225.8 1136.26   248.3 1129.64   265.1 1122.18   312.7 1095.02   332.7 1086.69
   388.6 1070.00   450.6 1049.66   586.5 1015.52   619.7 1006.05   653.5  997.88
   684.3  998.94   699.3  999.24   991.5 1004.25  1202.6 1005.43  1287.7 1004.68
  1345.5 1005.50  1376.8 1007.42  1434.1 1012.44  1494.1 1023.74  1518.7 1024.88
  1588.4 1038.77  1686.6 1054.01  1764.6 1063.37  1853.0 1080.22  1936.2 1098.43
#Mann= 3 , 0 , 0
       0     0.1       0   684.3   0.045       0   699.3     0.1       0
Bank Sta=   684.3,   699.3
Exp/Cntr=0.3,0.1

Type RM Length L Ch R = 1 ,26688,283.812,287.564,291.263
XS GIS Cut Line= 3
     1723464.291      243644.301     1723580.021      244084.154
     1723869.432      244984.340
#Sta/Elev= 30
       0 1064.73    48.4 1060.34   111.9 1056.75   211.0 1053.10   247.0 1049.52
   267.3 1045.03   276.3 1043.46   308.4 1035.98   382.0 1014.86   406.6 1008.50
   418.2 1006.54   442.9 1005.44   495.4  999.45   518.0  999.20   520.5  999.20
   535.5  999.24   608.9  999.72   742.5 1003.12   780.0 1011.68   804.9 1014.27
   917.7 1054.33  1009.9 1083.94  1039.0 1092.20  1046.3 1094.04  1187.6 1120.74
  1239.9 1133.24  1266.3 1138.59  1327.9 1152.48  1380.9 1166.45  1400.4 1170.32
#Mann= 3 , 0 , 0
       0     0.1       0   520.5   0.045       0   535.5     0.1       0
Bank Sta=   520.5,   535.5
Exp/Cntr=0.3,0.1

Type RM Length L Ch R = 1 ,26400.5,390.534,400,408.43
XS GIS Cut Line= 3
     1723321.841      243662.412     1723381.353      244327.017
     1723430.732      244814.104
#Sta/Elev= 30
       0 1058.84    90.5 1049.47   150.7 1045.29   185.8 1048.16   209.7 1046.65
   229.5 1043.57   262.6 1036.99   312.8 1025.98   343.2 1018.15   364.9 1014.11
   410.2 1006.89   445.9 1004.39   502.0 1001.57   528.1 1001.66   602.4 1003.57
   629.5 1003.44   650.8  999.74   659.8  999.44   670.8  999.36   674.8  999.45
   686.5  999.74   695.9 1001.73   717.4 1009.08   734.3 1015.39   758.7 1018.92
   799.6 1029.39   845.9 1043.31   955.3 1077.15  1027.4 1099.96  1156.8 1142.36
#Mann= 3 , 0 , 0
       0     0.1       0   659.8   0.045       0   674.8     0.1       0
Bank Sta=   659.8,   674.8
Exp/Cntr=0.3,0.1

Type RM Length L Ch R = 1 ,26000.5,335.85,330.064,325.579
XS GIS Cut Line= 3
     1723246.768      243541.103     1722992.848      244282.103
     1722855.799      244771.208
#Sta/Elev= 30
       0 1070.74   150.1 1051.15   244.3 1041.46   256.6 1041.11   310.3 1034.72
   453.3 1013.76   486.9 1010.36   543.9 1007.12   623.8 1004.09   666.2 1003.41
   724.0 1001.52   741.8 1002.04   751.2 1001.55   766.3 1000.09   775.8  999.70
   776.2  999.68   790.8 1002.13   828.8 1008.18   855.3 1011.24   924.8 1016.70
   944.7 1020.27   998.0 1028.05  1010.2 1030.68  1027.9 1035.48  1068.3 1048.93
  1084.1 1055.01  1120.9 1064.29  1146.8 1070.13  1219.8 1080.62  1291.2 1093.11
#Mann= 3 , 0 , 0
       0     0.1       0   775.8   0.045       0   790.8     0.1       0
Bank Sta=   775.8,   790.8
Exp/Cntr=0.3,0.1

Type RM Length L Ch R = 1 ,25670.4,611.161,594.891,576.95
XS GIS Cut Line= 3
     1722993.082      242449.483     1722669.932      244218.707
     1722624.084      244794.159
#Sta/Elev= 30
       0 1230.83    95.3 1205.17   153.9 1183.97   178.1 1179.05   223.0 1178.37
   242.9 1174.11   371.2 1128.07   519.8 1121.34   552.2 1115.57   629.5 1095.46
   703.8 1081.09   761.1 1072.12   833.6 1066.14  1039.8 1032.72  1106.4 1024.90
  1267.3 1022.76  1335.0 1015.19  1405.1 1001.26  1642.0 1003.45  1768.7 1000.67
  1813.7 1003.61  1828.7 1004.55  1864.3 1006.34  1890.7 1019.96  1902.4 1023.09
  2004.5 1028.90  2033.0 1033.68  2051.6 1032.07  2246.3 1069.61  2375.8 1083.76
#Mann= 3 , 0 , 0
       0     0.1       0  1813.7   0.045       0  1828.7     0.1       0
Bank Sta=  1813.7,  1828.7
Exp/Cntr=0.3,0.1

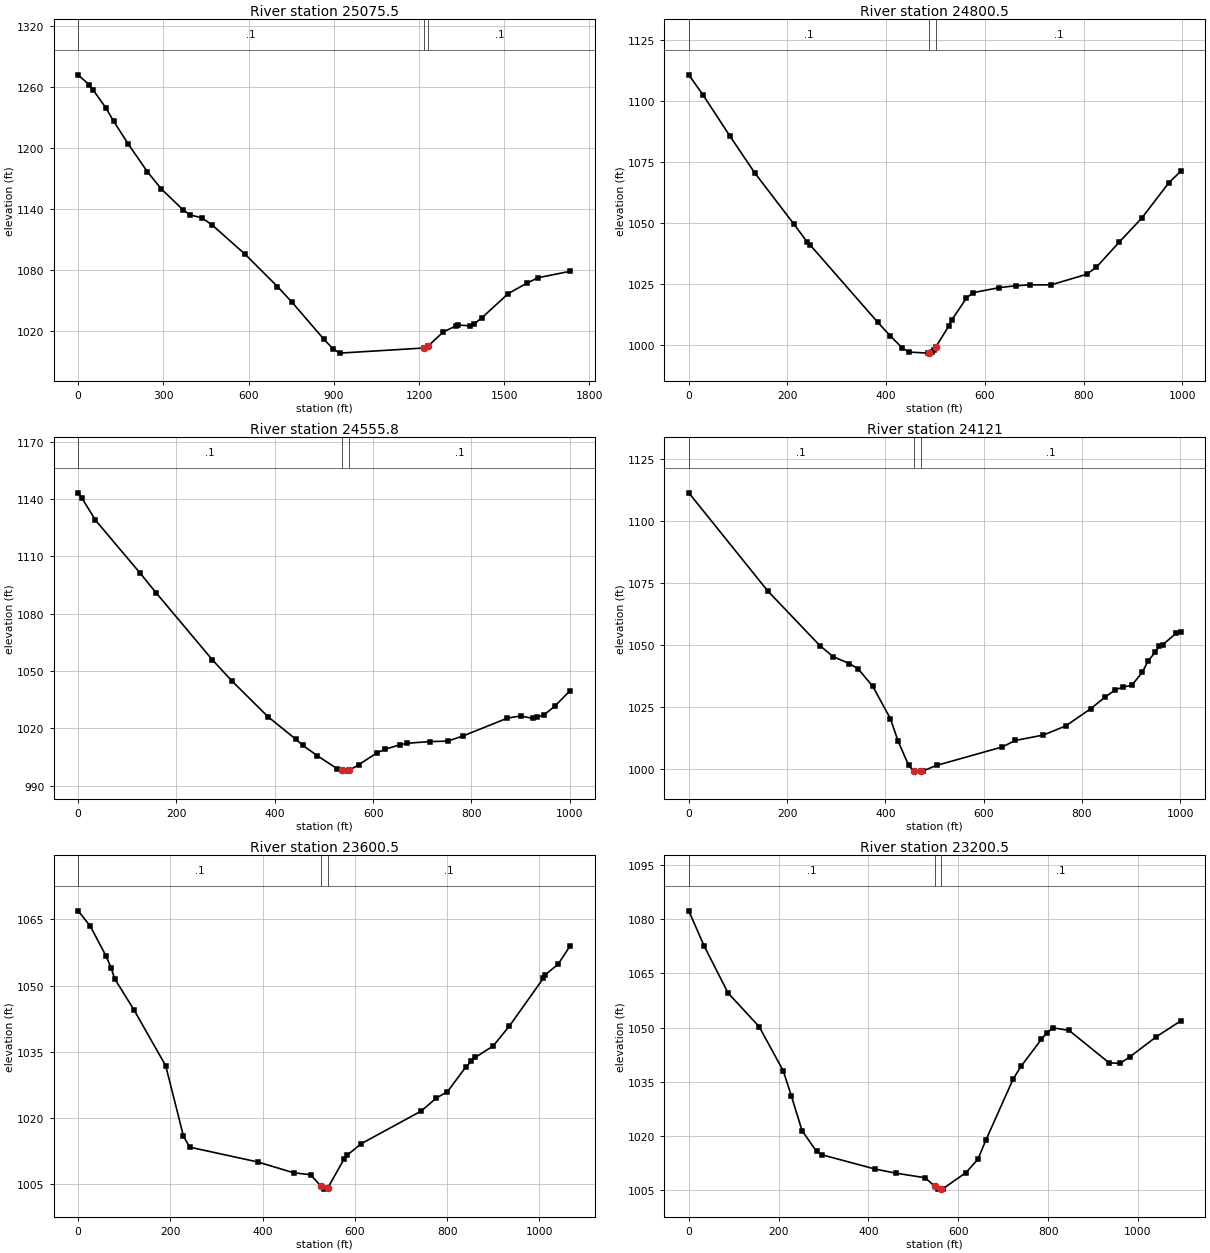
Type RM Length L Ch R = 1 ,25075.5,278.572,275.046,268.712
XS GIS Cut Line= 3
     1721332.589      243548.790     1722201.273      244432.849
     1722511.077      244816.273
#Sta/Elev= 30
       0 1271.74    38.1 1262.15    52.7 1256.87    96.7 1239.63   124.9 1226.22
   177.1 1203.45   244.0 1176.48   291.6 1159.99   368.9 1139.24   393.1 1134.21
   435.5 1131.26   471.9 1124.22   587.7 1095.52   701.8 1063.75   752.7 1048.47
   864.6 1012.18   896.6 1002.77   920.7  998.35  1218.5 1003.40  1233.5 1005.63
  1285.6 1019.17  1329.4 1024.98  1337.4 1025.93  1380.8 1025.16  1392.5 1026.55
  1422.5 1033.30  1513.5 1056.64  1580.5 1067.22  1620.0 1072.46  1732.4 1078.76
#Mann= 3 , 0 , 0
       0     0.1       0  1218.5   0.045       0  1233.5     0.1       0
Bank Sta=  1218.5,  1233.5
Exp/Cntr=0.3,0.1

Type RM Length L Ch R = 1 ,24800.5,246.573,244.611,244.298
XS GIS Cut Line= 3
     1721551.855      244263.980     1721954.731      244549.324
     1722385.772      244809.534
#Sta/Elev= 30
       0 1110.79    28.8 1102.57    83.4 1085.66   133.5 1070.62   213.6 1049.41
   239.5 1042.35   246.3 1040.92   382.5 1009.39   408.0 1003.78   431.9  998.92
   445.5  997.07   485.7  996.63   486.2  996.66   493.4  997.13   497.3  998.04
   501.2  999.32   526.7 1007.69   532.7 1010.14   562.7 1019.21   576.3 1021.43
   629.0 1023.49   662.5 1024.26   691.0 1024.65   733.7 1024.61   806.1 1028.95
   826.2 1031.90   872.7 1042.24   917.9 1051.97   973.0 1066.53   997.2 1071.24
#Mann= 3 , 0 , 0
       0     0.1       0   486.2   0.045       0   501.2     0.1       0
Bank Sta=   486.2,   501.2
Exp/Cntr=0.3,0.1

Type RM Length L Ch R = 1 ,24555.8,438.766,434.802,430.839
XS GIS Cut Line= 3
     1721384.450      244500.427     1721818.299      244750.016
     1722250.138      245003.021
#Sta/Elev= 30
       0 1143.24     7.7 1140.47    35.3 1128.92   125.9 1101.30   158.4 1091.00
   272.9 1055.91   312.1 1045.00   386.1 1026.12   442.3 1014.44   457.1 1011.12
   486.7 1005.68   527.6  998.78   536.2  998.28   548.6  997.64   551.2  998.03
   570.7 1000.98   608.2 1007.22   624.6 1009.08   654.3 1011.41   669.2 1012.21
   715.2 1013.10   751.7 1013.32   782.7 1016.01   873.2 1025.35   900.0 1026.51
   925.8 1025.20   933.6 1025.81   948.6 1027.24   969.4 1031.53  1001.0 1039.76
#Mann= 3 , 0 , 0
       0     0.1       0   536.2   0.045       0   551.2     0.1       0
Bank Sta=   536.2,   551.2
Exp/Cntr=0.3,0.1

Type RM Length L Ch R = 1 ,24121,516.164,520.587,521.211
XS GIS Cut Line= 3
     1721222.178      244997.264     1721691.534      245170.918
     1722155.708      245358.863
#Sta/Elev= 30
       0 1111.31   160.7 1071.77   266.6 1049.78   294.1 1045.26   327.0 1042.52
   344.7 1040.36   374.5 1033.30   410.2 1020.34   426.1 1011.18   447.2 1001.59
   457.4  999.18   472.4  999.25   476.5  999.25   504.4 1001.50   638.3 1008.94
   664.2 1011.53   721.4 1013.71   767.0 1017.38   818.2 1024.37   846.3 1028.90
   868.0 1031.95   883.9 1033.04   901.6 1033.78   922.7 1039.00   934.4 1043.47
   949.3 1047.16   957.7 1049.66   965.1 1050.18   991.9 1054.80  1001.2 1055.20
#Mann= 3 , 0 , 0
       0     0.1       0   457.4   0.045       0   472.4     0.1       0
Bank Sta=   457.4,   472.4
Exp/Cntr=0.3,0.1

Type RM Length L Ch R = 1 ,23600.5,396.456,400,408.691
XS GIS Cut Line= 3
     1721056.976      245381.379     1721514.796      245656.729
     1722009.086      245855.030
#Sta/Elev= 30
       0 1066.92    26.1 1063.49    60.2 1056.74    71.3 1054.05    79.1 1051.55
   120.7 1044.54   189.9 1031.81   228.4 1015.85   241.8 1013.38   389.9 1010.01
   467.4 1007.57   504.0 1007.13   526.7 1004.53   533.1 1003.87   541.7 1004.21
   576.2 1010.61   582.6 1011.51   614.0 1014.17   744.0 1021.57   776.1 1024.47
   800.8 1025.96   840.9 1031.59   852.4 1032.81   861.5 1033.74   899.9 1036.31
   934.9 1040.80  1008.5 1051.62  1011.9 1052.37  1040.6 1054.81  1066.8 1058.99
#Mann= 3 , 0 , 0
       0     0.1       0   526.7   0.045       0   541.7     0.1       0
Bank Sta=   526.7,   541.7
Exp/Cntr=0.3,0.1

Type RM Length L Ch R = 1 ,23200.5,344.098,336.897,328.349
XS GIS Cut Line= 3
     1720802.154      245524.469     1721216.381      245894.035
     1721600.418      246274.053
#Sta/Elev= 30
       0 1082.37    34.1 1072.65    87.6 1059.55   156.5 1050.28   210.4 1037.97
   228.6 1030.94   252.1 1021.43   284.4 1015.64   296.5 1014.71   415.6 1010.73
   461.4 1009.61   526.4 1008.34   547.6 1005.95   554.1 1005.19   562.6 1005.30
   566.4 1005.35   617.2 1009.79   643.7 1013.47   661.5 1018.81   722.2 1035.74
   740.0 1039.30   785.2 1046.75   797.8 1048.59   811.5 1049.92   846.6 1049.20
   935.7 1040.23   960.2 1040.07   981.7 1041.84  1041.2 1047.48  1095.4 1051.85
#Mann= 3 , 0 , 0
       0     0.1       0   547.6   0.045       0   562.6     0.1       0
Bank Sta=   547.6,   562.6
Exp/Cntr=0.3,0.1

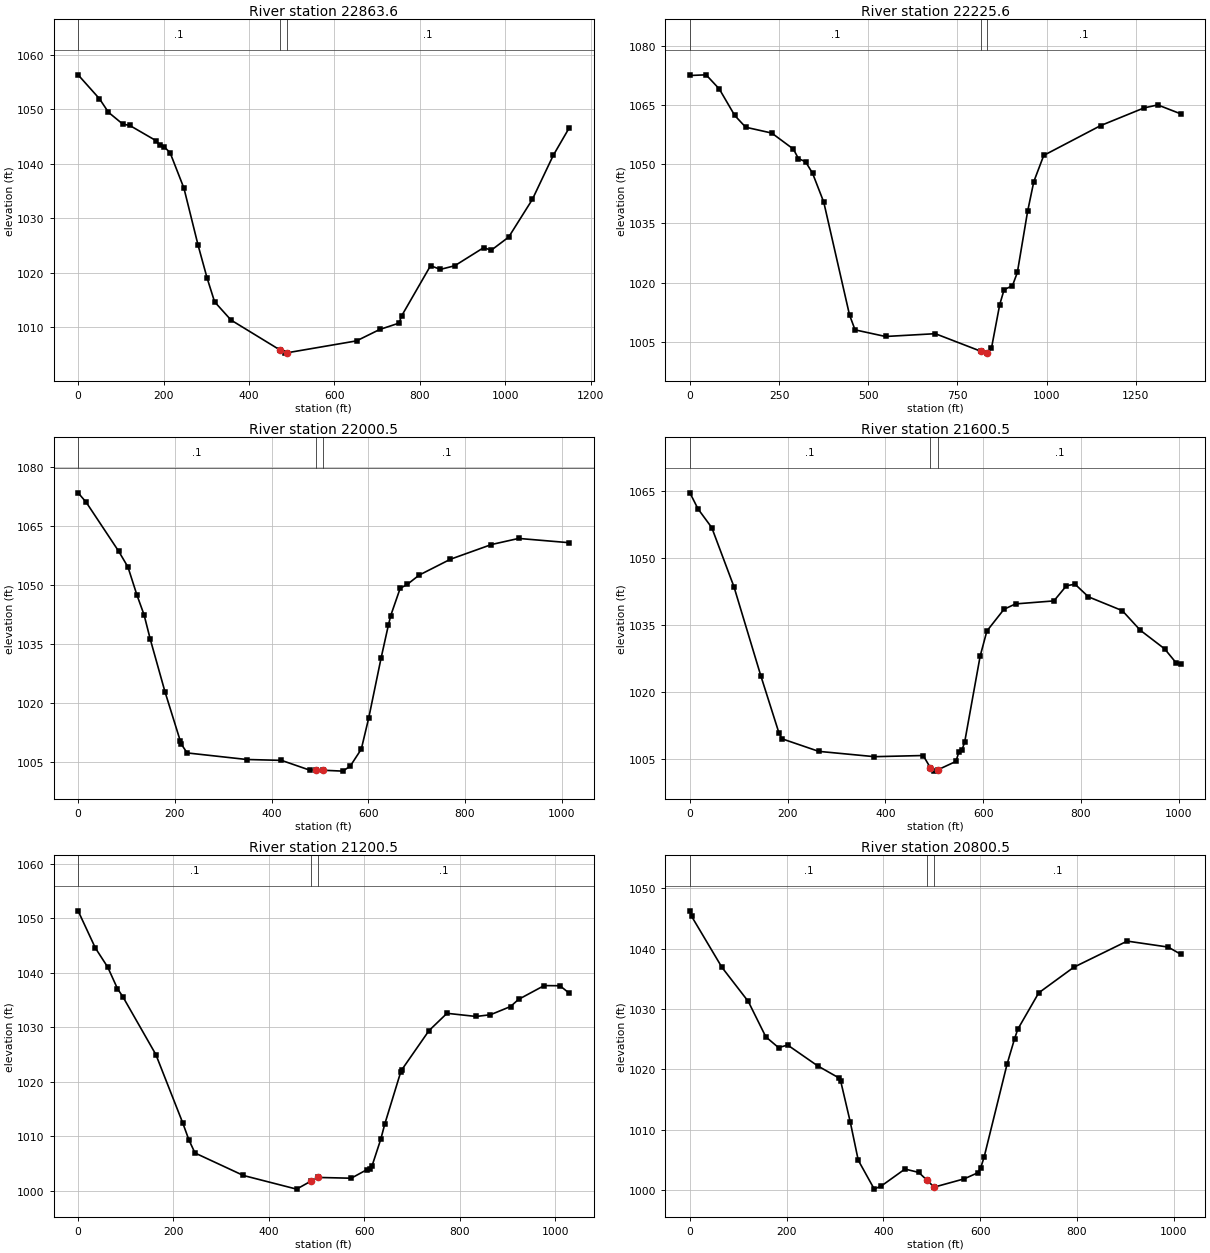
Type RM Length L Ch R = 1 ,22863.6,635.849,637.911,640.956
XS GIS Cut Line= 3
     1720513.254      245801.235     1720879.356      246035.360
     1721525.152      246342.076
#Sta/Elev= 30
       0 1056.32    50.0 1051.93    71.1 1049.44   104.7 1047.27   121.1 1047.02
   182.5 1044.23   190.7 1043.36   201.3 1043.11   215.3 1042.04   247.8 1035.51
   281.0 1025.02   302.0 1019.02   319.6 1014.64   358.1 1011.29   473.5 1005.76
   484.6 1005.22   488.5 1005.27   652.0 1007.47   706.1 1009.56   751.4 1010.73
   757.6 1012.07   825.2 1021.27   848.3 1020.60   881.8 1021.26   949.9 1024.60
   967.1 1024.10  1008.2 1026.53  1063.5 1033.43  1112.4 1041.51  1149.5 1046.53
#Mann= 3 , 0 , 0
       0     0.1       0   473.5   0.045       0   488.5     0.1       0
Bank Sta=   473.5,   488.5
Exp/Cntr=0.3,0.1

Type RM Length L Ch R = 1 ,22225.6,227.941,225.192,226.606
XS GIS Cut Line= 3
     1720210.220      246239.403     1720963.591      246531.527
     1721455.589      246815.963
#Sta/Elev= 30
       0 1072.45    45.4 1072.62    82.2 1069.06   125.7 1062.33   156.3 1059.36
   229.4 1057.88   290.1 1053.82   304.2 1051.42   324.3 1050.61   343.8 1047.71
   375.2 1040.40   447.4 1011.85   462.9 1008.07   548.3 1006.39   687.9 1007.10
   817.1 1002.60   832.1 1002.22   833.6 1002.18   845.4 1003.45   868.4 1014.43
   880.7 1018.23   904.2 1019.25   917.9 1022.59   946.6 1038.03   964.0 1045.58
   991.9 1052.23  1151.4 1059.77  1273.2 1064.25  1311.6 1065.00  1376.3 1062.73
#Mann= 3 , 0 , 0
       0     0.1       0   817.1   0.045       0   832.1     0.1       0
Bank Sta=   817.1,   832.1
Exp/Cntr=0.3,0.1

Type RM Length L Ch R = 1 ,22000.5,398.984,400,393.279
XS GIS Cut Line= 3
     1720373.112      246535.921     1720840.280      246713.492
     1721269.224      246998.954
#Sta/Elev= 30
       0 1073.35    16.6 1070.98    84.0 1058.51   103.1 1054.52   121.8 1047.36
   136.3 1042.44   149.2 1036.21   179.5 1022.93   211.1 1010.47   213.4 1009.59
   225.4 1007.36   348.7 1005.69   420.5 1005.47   479.4 1002.97   492.3 1003.06
   507.3 1002.96   547.2 1002.74   562.5 1003.98   585.5 1008.32   600.8 1016.20
   626.3 1031.36   641.4 1039.73   646.4 1042.22   665.8 1049.10   680.8 1050.14
   705.1 1052.47   769.8 1056.50   854.6 1060.23   910.8 1061.78  1015.0 1060.70
#Mann= 3 , 0 , 0
       0     0.1       0   492.3   0.045       0   507.3     0.1       0
Bank Sta=   492.3,   507.3
Exp/Cntr=0.3,0.1

Type RM Length L Ch R = 1 ,21600.5,404.787,400,404.375
XS GIS Cut Line= 3
     1720236.099      246888.908     1720695.519      247085.571
     1721179.227      247229.895
#Sta/Elev= 30
       0 1064.48    16.6 1060.88    44.7 1056.71    90.1 1043.49   145.0 1023.61
   182.0 1010.87   188.3 1009.50   263.5 1006.69   377.6 1005.50   477.3 1005.76
   492.2 1002.99   498.5 1002.27   507.2 1002.56   544.2 1004.44   550.2 1006.49
   556.6 1006.99   562.1 1008.73   593.8 1027.96   607.6 1033.59   642.6 1038.45
   666.2 1039.65   744.7 1040.32   770.3 1043.70   787.9 1044.06   815.4 1041.23
   884.7 1038.14   921.4 1033.77   971.2 1029.61   994.6 1026.50  1004.5 1026.32
#Mann= 3 , 0 , 0
       0     0.1       0   492.2   0.045       0   507.2     0.1       0
Bank Sta=   492.2,   507.2
Exp/Cntr=0.3,0.1

Type RM Length L Ch R = 1 ,21200.5,409.457,400,387.594
XS GIS Cut Line= 3
     1720017.083      247301.394     1720503.662      247399.728
     1720981.107      247636.374
#Sta/Elev= 30
       0 1051.34    36.2 1044.53    62.2 1041.01    82.6 1037.07    93.7 1035.62
   163.0 1025.01   219.3 1012.50   232.3 1009.36   245.1 1006.96   346.6 1002.84
   458.1 1000.34   488.9 1001.84   503.9 1002.48   572.6 1002.34   604.9 1003.88
   612.3 1003.97   616.5 1004.66   634.6 1009.49   643.1 1012.30   676.2 1021.75
   678.6 1022.21   735.7 1029.39   773.4 1032.56   834.4 1031.98   864.6 1032.30
   906.6 1033.80   923.4 1035.11   977.2 1037.64  1010.3 1037.61  1029.3 1036.27
#Mann= 3 , 0 , 0
       0     0.1       0   488.9   0.045       0   503.9     0.1       0
Bank Sta=   488.9,   503.9
Exp/Cntr=0.3,0.1

Type RM Length L Ch R = 1 ,20800.5,400.562,400,393.257
XS GIS Cut Line= 3
     1719958.983      247884.129     1720444.779      247776.672
     1720961.551      247746.855
#Sta/Elev= 30
       0 1046.28     3.7 1045.34    66.2 1036.91   120.7 1031.25   157.0 1025.38
   183.2 1023.60   202.2 1024.02   264.0 1020.58   307.9 1018.58   311.6 1018.11
   331.5 1011.29   348.1 1004.92   381.2 1000.13   396.1 1000.67   444.7 1003.46
   473.2 1002.90     490 1001.63     505 1000.46   567.0 1001.83   595.3 1002.84
   601.1 1003.63   608.2 1005.39   655.9 1020.88   671.3 1025.06   678.0 1026.65
   721.3 1032.68   793.9 1036.93   904.2 1041.26   988.9 1040.27  1015.2 1039.07
#Mann= 3 , 0 , 0
       0     0.1       0     490   0.045       0     505     0.1       0
Bank Sta=     490,     505
Exp/Cntr=0.3,0.1

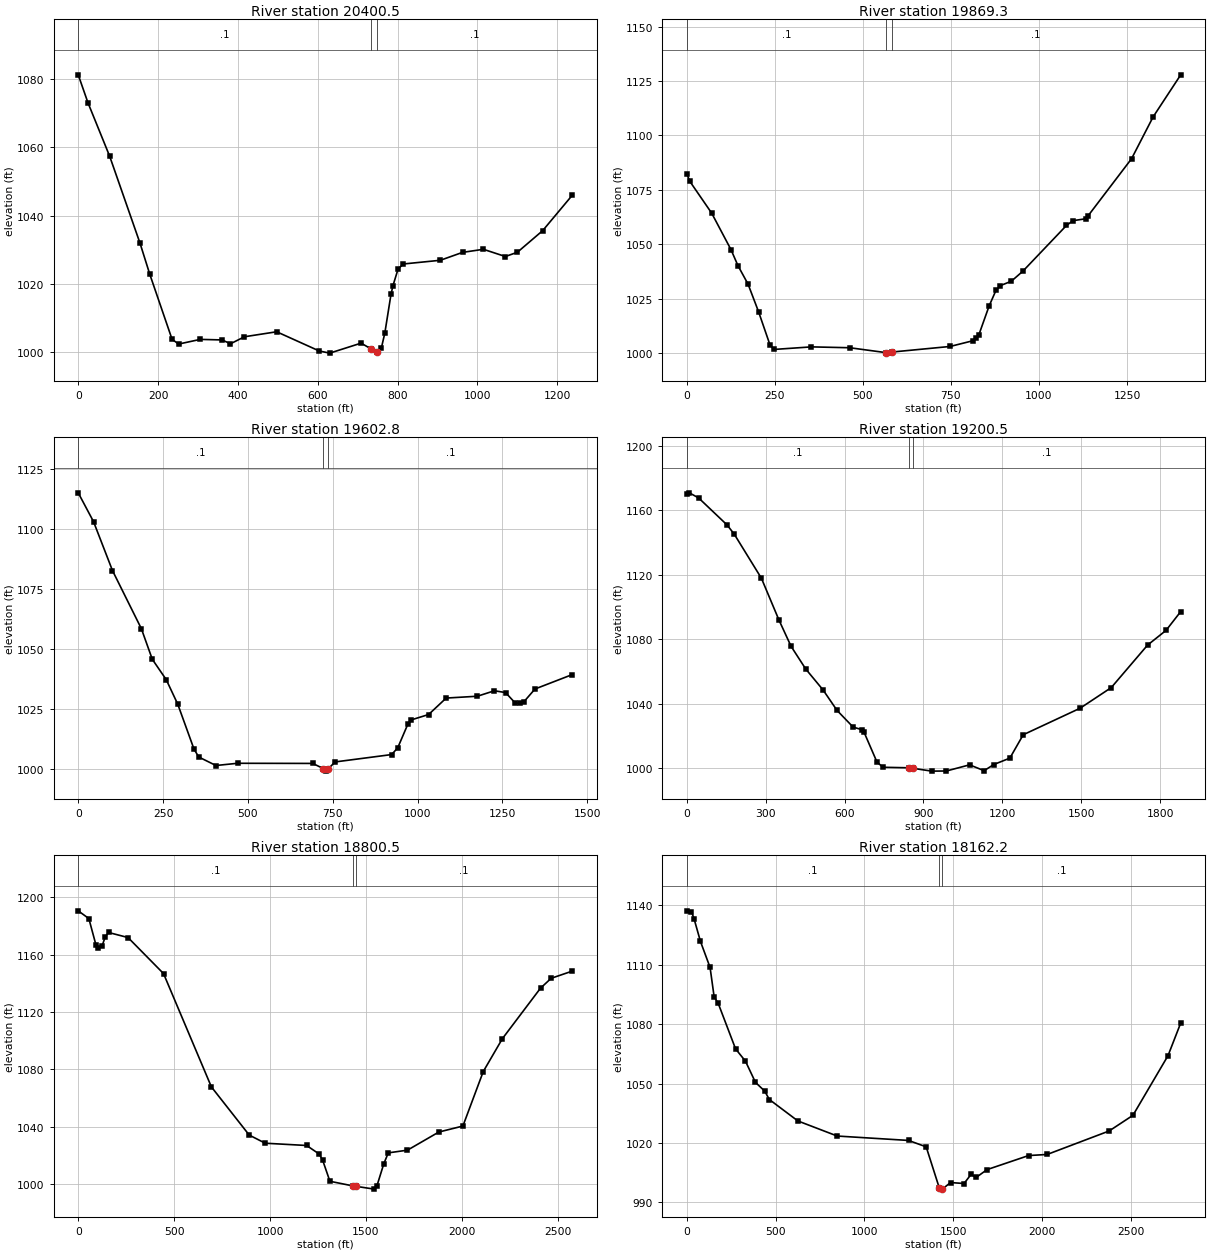
Type RM Length L Ch R = 1 ,20400.5,519.637,531.136,545.192
XS GIS Cut Line= 3
     1719848.669      248331.114     1720567.031      248152.572
     1721032.844      247979.638
#Sta/Elev= 30
       0 1081.21    24.3 1073.06    78.8 1057.37   155.0 1031.86   179.1 1022.90
   235.0 1003.84   251.4 1002.43   305.7 1003.80   360.3 1003.64   381.4 1002.52
   416.4 1004.57   497.1 1006.03   603.7 1000.41   630.0  999.78   708.5 1002.70
   732.7 1001.08   747.7 1000.07   759.2 1001.22   768.0 1005.65   783.4 1016.96
   788.3 1019.49   801.2 1024.39   814.2 1025.86   907.1 1026.95   962.7 1029.26
  1014.9 1030.16  1069.9 1028.05  1100.0 1029.29  1163.4 1035.62  1237.1 1045.92
#Mann= 3 , 0 , 0
       0     0.1       0   732.7   0.045       0   747.7     0.1       0
Bank Sta=   732.7,   747.7
Exp/Cntr=0.3,0.1

Type RM Length L Ch R = 1 ,19869.3,259.411,266.55,273.688
XS GIS Cut Line= 3
     1719900.559      248508.406     1720555.889      248686.347
     1721262.682      248841.370
#Sta/Elev= 30
       0 1082.32     8.6 1078.91    70.4 1064.38   125.4 1047.58   145.2 1040.23
   173.9 1031.73   203.6 1019.12   235.7 1004.05   247.3 1001.78   353.9 1002.96
   462.8 1002.56   566.4 1000.30   574.9 1000.09   581.4 1000.57   747.7 1003.15
   812.0 1005.76   821.6 1007.20   829.2 1008.42   858.4 1021.70   877.8 1028.86
   890.6 1031.09   921.7 1033.11   954.5 1037.73  1078.1 1058.69  1096.6 1060.90
  1133.0 1061.77  1138.2 1062.83  1263.1 1089.35  1324.3 1108.54  1402.7 1127.85
#Mann= 3 , 0 , 0
       0     0.1       0   566.4   0.045       0   581.4     0.1       0
Bank Sta=   566.4,   581.4
Exp/Cntr=0.3,0.1

Type RM Length L Ch R = 1 ,19602.8,398.298,402.314,405.829
XS GIS Cut Line= 3
     1719809.751      248521.379     1720686.842      249083.765
     1721094.278      249152.952
#Sta/Elev= 30
       0 1115.26    45.1 1103.24   100.9 1082.86   186.1 1058.61   218.2 1045.89
   259.2 1037.42   293.3 1027.15   341.2 1008.41   355.3 1005.15   405.8 1001.62
   469.4 1002.55   690.8 1002.49   722.2 1000.35   730.4  999.28   737.2 1000.32
   756.8 1003.11   923.3 1006.18   941.3 1008.98   970.9 1018.77   980.7 1020.61
  1032.3 1022.87  1084.1 1029.73  1175.9 1030.49  1226.3 1032.77  1259.1 1032.02
  1286.6 1027.80  1302.2 1027.49  1312.5 1028.09  1345.8 1033.51  1455.1 1039.49
#Mann= 3 , 0 , 0
       0     0.1       0   722.2   0.045       0   737.2     0.1       0
Bank Sta=   722.2,   737.2
Exp/Cntr=0.3,0.1

Type RM Length L Ch R = 1 ,19200.5,381.596,400,400.985
XS GIS Cut Line= 4
     1719462.688      248530.459     1719731.203      248781.951
     1720084.641      249112.981     1720848.279      249798.699
#Sta/Elev= 30
       0 1170.21     9.4 1170.73    44.8 1167.55   153.3 1150.75   181.0 1144.90
   283.5 1117.77   350.3 1091.83   396.4 1075.52   452.0 1061.48   518.3 1048.41
   571.2 1035.78   632.3 1025.43   667.1 1023.74   673.9 1022.28   723.0 1003.78
   745.6 1000.49   844.6 1000.17   859.6  999.86   931.5  998.10   987.0  998.18
  1075.4 1002.00  1130.7  998.37  1167.5 1002.20  1228.6 1006.16  1279.4 1020.66
  1495.7 1037.11  1614.3 1049.92  1752.3 1076.26  1822.7 1085.41  1878.5 1097.06
#Mann= 3 , 0 , 0
       0     0.1       0   844.6   0.045       0   859.6     0.1       0
Bank Sta=   844.6,   859.6
Exp/Cntr=0.3,0.1

Type RM Length L Ch R = 1 ,18800.5,647.927,638.247,646.488
XS GIS Cut Line= 3
     1719123.548      248373.539     1720049.595      249477.186
     1720931.509      250190.192
#Sta/Elev= 30
       0 1190.56    55.3 1185.17    92.2 1166.86   105.2 1164.44   124.6 1166.23
   141.4 1172.62   158.3 1175.46   259.6 1171.94   444.8 1146.80   694.2 1067.86
   891.4 1034.29   974.8 1028.61  1190.7 1027.02  1255.9 1021.10  1274.3 1016.78
  1312.1 1002.08  1433.2  998.82  1448.2  998.55  1543.7  996.61  1556.6  998.60
  1593.3 1014.39  1616.5 1021.88  1716.5 1023.77  1879.8 1036.39  2005.5 1040.58
  2111.6 1078.55  2211.6 1101.52  2410.1 1136.66  2465.5 1143.53  2574.8 1148.51
#Mann= 3 , 0 , 0
       0     0.1       0  1433.2   0.045       0  1448.2     0.1       0
Bank Sta=  1433.2,  1448.2
Exp/Cntr=0.3,0.1

Type RM Length L Ch R = 1 ,18162.2,482.677,476.536,470.394
XS GIS Cut Line= 2
     1719036.627      248616.919     1720192.679      251146.325
#Sta/Elev= 30
       0 1137.25    26.0 1136.83    40.3 1133.30    76.6 1121.79   130.8 1108.63
   153.5 1093.88   176.7 1090.48   274.2 1067.56   330.1 1061.30   386.3 1050.62
   438.5 1046.19   464.5 1041.96   625.2 1031.13   847.0 1023.51  1248.2 1021.29
  1347.7 1018.06  1421.4  997.34  1436.4  996.78  1438.4  996.70  1484.9 1000.02
  1560.9  999.54  1600.5 1004.15  1628.8 1002.58  1690.4 1006.55  1924.6 1013.66
  2028.7 1014.20  2378.0 1026.07  2512.0 1033.97  2709.6 1064.11  2781.1 1080.61
#Mann= 3 , 0 , 0
       0     0.1       0  1421.4   0.045       0  1436.4     0.1       0
Bank Sta=  1421.4,  1436.4
Exp/Cntr=0.3,0.1

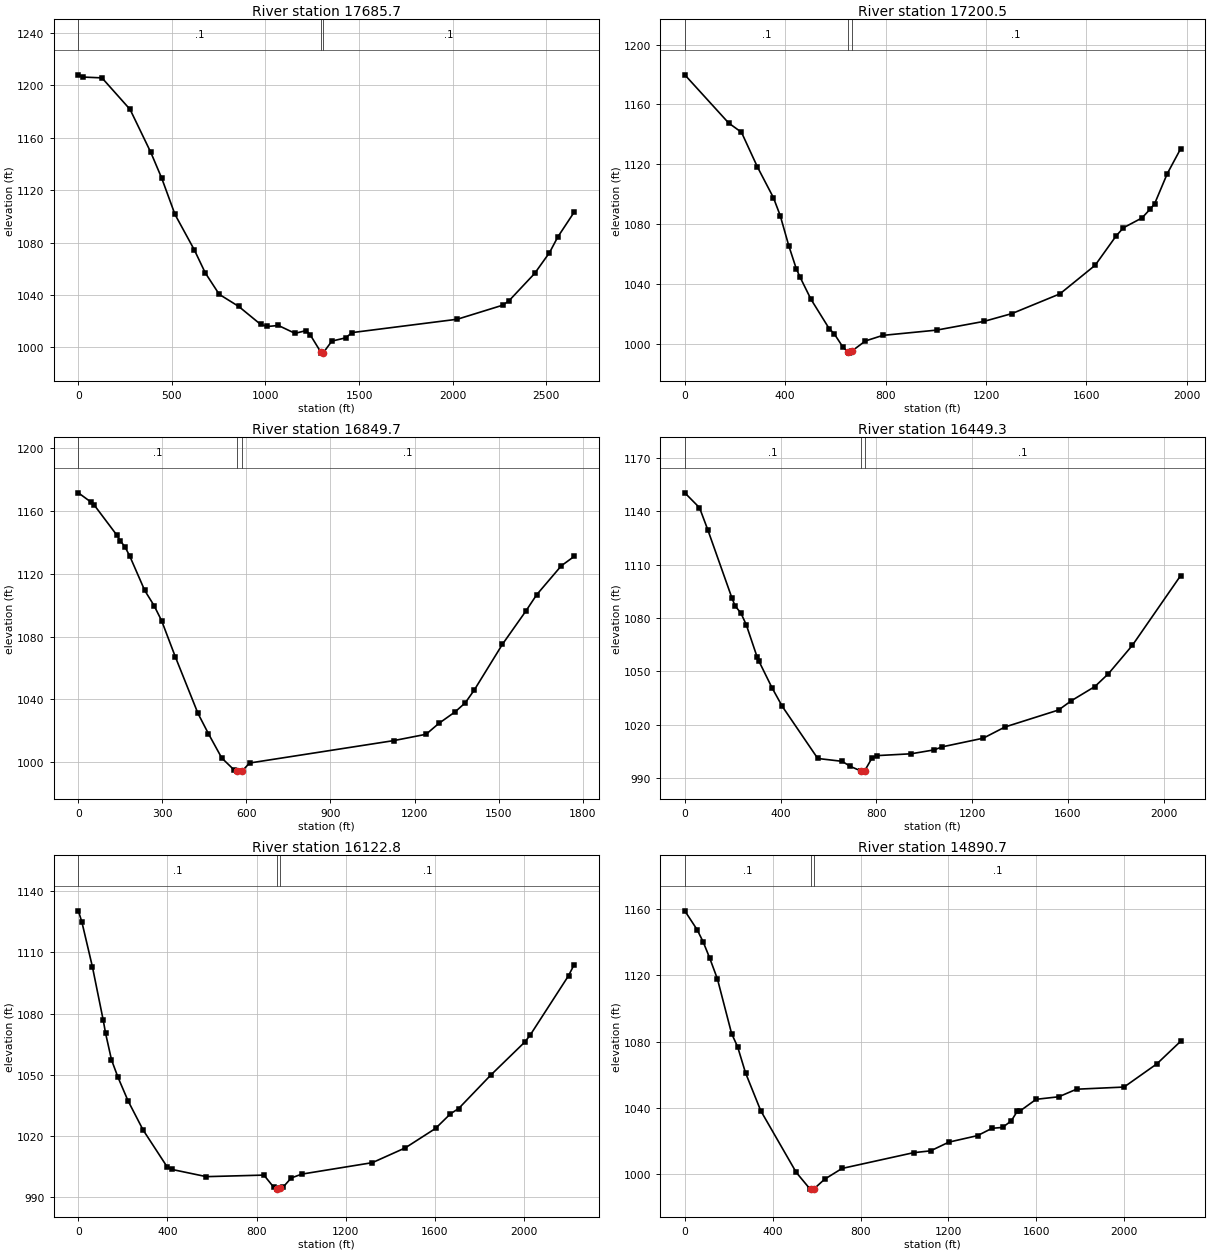
Type RM Length L Ch R = 1 ,17685.7,488.195,485.217,483.768
XS GIS Cut Line= 2
     1718411.403      249166.404     1720115.105      251195.813
#Sta/Elev= 30
       0 1208.12    27.2 1206.40   126.3 1205.79   276.5 1181.69   387.5 1148.80
   446.0 1129.03   516.5 1101.48   620.2 1074.30   678.2 1056.87   753.0 1040.44
   857.1 1031.20   974.1 1017.49  1010.9 1015.89  1069.2 1016.65  1158.0 1010.64
  1217.4 1012.75  1239.2 1009.51  1294.3  996.67  1298.6  995.53  1309.3  995.88
  1354.9 1004.73  1427.8 1007.16  1463.0 1011.22  2025.5 1021.43  2268.8 1032.19
  2302.5 1035.68  2438.5 1056.38  2517.9 1072.30  2562.5 1084.33  2649.7 1103.21
#Mann= 3 , 0 , 0
       0     0.1       0  1294.3   0.045       0  1309.3     0.1       0
Bank Sta=  1294.3,  1309.3
Exp/Cntr=0.3,0.1

Type RM Length L Ch R = 1 ,17200.5,346.876,350.724,350.442
XS GIS Cut Line= 4
     1718393.411      250016.349     1718877.693      250460.451
     1719241.594      250842.002     1719787.403      251414.285
#Sta/Elev= 30
       0 1179.77   174.9 1147.56   225.7 1141.41   289.4 1118.22   353.1 1097.71
   380.2 1085.72   414.0 1065.74   443.8 1050.42   458.4 1044.91   502.5 1029.90
   575.1 1010.29   594.6 1006.96   630.8  997.71   649.6  994.78   655.5  993.90
   664.6  995.15   719.3 1002.02   788.8 1005.75  1003.1 1009.27  1191.9 1015.10
  1303.1 1020.31  1494.3 1033.48  1634.8 1052.60  1718.5 1072.23  1747.6 1077.65
  1821.4 1084.20  1855.0 1090.29  1871.7 1093.70  1922.0 1113.78  1975.2 1130.36
#Mann= 3 , 0 , 0
       0     0.1       0   649.6   0.045       0   664.6     0.1       0
Bank Sta=   649.6,   664.6
Exp/Cntr=0.3,0.1

Type RM Length L Ch R = 1 ,16849.7,389.566,400.465,413.87
XS GIS Cut Line= 4
     1718354.610      250312.784     1718715.019      250763.871
     1719060.139      251107.345     1719607.390      251552.643
#Sta/Elev= 30
       0 1171.61    45.1 1165.73    57.5 1163.63   138.0 1144.53   149.1 1141.21
   166.5 1137.17   183.6 1131.29   237.0 1109.41   270.2 1099.82   297.4 1090.09
   346.2 1067.14   427.1 1031.06   464.5 1018.12   511.9 1002.69   557.1  994.87
   567.7  994.61   582.7  994.34   584.3  994.31   611.3  999.48  1126.1 1013.76
  1241.3 1017.79  1286.6 1024.69  1344.6 1032.03  1381.1 1037.82  1413.2 1045.95
  1513.9 1075.15  1596.7 1096.10  1636.2 1106.73  1724.1 1125.14  1769.8 1131.08
#Mann= 3 , 0 , 0
       0     0.1       0   567.7   0.045       0   582.7     0.1       0
Bank Sta=   567.7,   582.7
Exp/Cntr=0.3,0.1

Type RM Length L Ch R = 1 ,16449.3,324.035,326.463,319.21
XS GIS Cut Line= 3
     1718285.810      250377.908     1718588.164      251428.442
     1719132.241      252241.531
#Sta/Elev= 30
       0 1150.47    61.4 1142.10    95.9 1129.72   196.8 1091.31   209.6 1086.95
   234.8 1082.67   256.7 1076.23   302.1 1058.07   308.4 1056.07   363.9 1040.85
   407.3 1030.25   555.5 1000.93   657.3  999.33   691.4  996.48     737  993.84
   737.6  993.81     752  994.09   782.0 1001.17   801.0 1002.53   945.4 1003.57
  1041.8 1005.77  1075.5 1007.48  1246.9 1012.35  1337.9 1018.67  1561.4 1028.21
  1615.3 1033.46  1713.3 1041.42  1770.0 1048.67  1869.8 1064.61  2071.5 1103.85
#Mann= 3 , 0 , 0
       0     0.1       0     737   0.045       0     752     0.1       0
Bank Sta=     737,     752
Exp/Cntr=0.3,0.1

Type RM Length L Ch R = 1 ,16122.8,1220.366,1232.064,1253.54
XS GIS Cut Line= 4
     1718214.152      250421.595     1718176.108      250902.945
     1718254.337      251311.475     1718906.246      252467.526
#Sta/Elev= 30
       0 1130.38    16.0 1124.86    63.0 1103.04   111.9 1076.68   122.5 1070.25
   148.9 1057.32   177.5 1048.89   223.3 1037.18   290.5 1022.97   398.4 1004.89
   420.4 1003.57   574.7 1000.04   833.2 1000.80   876.6  994.92   892.2  993.95
   892.6  993.92   907.2  994.39   918.3  994.79   956.0  999.40  1003.1 1001.28
  1320.0 1006.90  1467.7 1014.14  1603.5 1023.67  1670.8 1030.86  1707.5 1033.45
  1851.1 1049.78  2003.9 1065.99  2027.8 1069.32  2200.6 1098.53  2226.0 1104.02
#Mann= 3 , 0 , 0
       0     0.1       0   892.2   0.045       0   907.2     0.1       0
Bank Sta=   892.2,   907.2
Exp/Cntr=0.3,0.1

Type RM Length L Ch R = 1 ,14890.7,473.69,468.03,460.26
XS GIS Cut Line= 3
     1718223.128      250290.743     1717983.139      250711.758
     1717248.366      252324.784
#Sta/Elev= 30
       0 1158.98    56.4 1147.53    83.9 1140.15   113.5 1130.41   148.6 1117.82
   213.0 1084.91   240.5 1076.88   276.4 1061.18   345.9 1038.25   507.4 1001.05
   570.5  990.97   574.1  991.02   589.1  991.25   636.2  996.92   715.6 1003.45
  1041.2 1012.97  1119.0 1014.08  1202.0 1019.34  1332.5 1023.27  1398.8 1027.70
  1446.5 1028.21  1486.3 1032.19  1512.9 1037.84  1527.8 1038.32  1599.4 1045.19
  1702.6 1046.73  1783.2 1051.29  1999.6 1052.59  2149.0 1066.60  2257.1 1080.21
#Mann= 3 , 0 , 0
       0     0.1       0   574.1   0.045       0   589.1     0.1       0
Bank Sta=   574.1,   589.1
Exp/Cntr=0.3,0.1