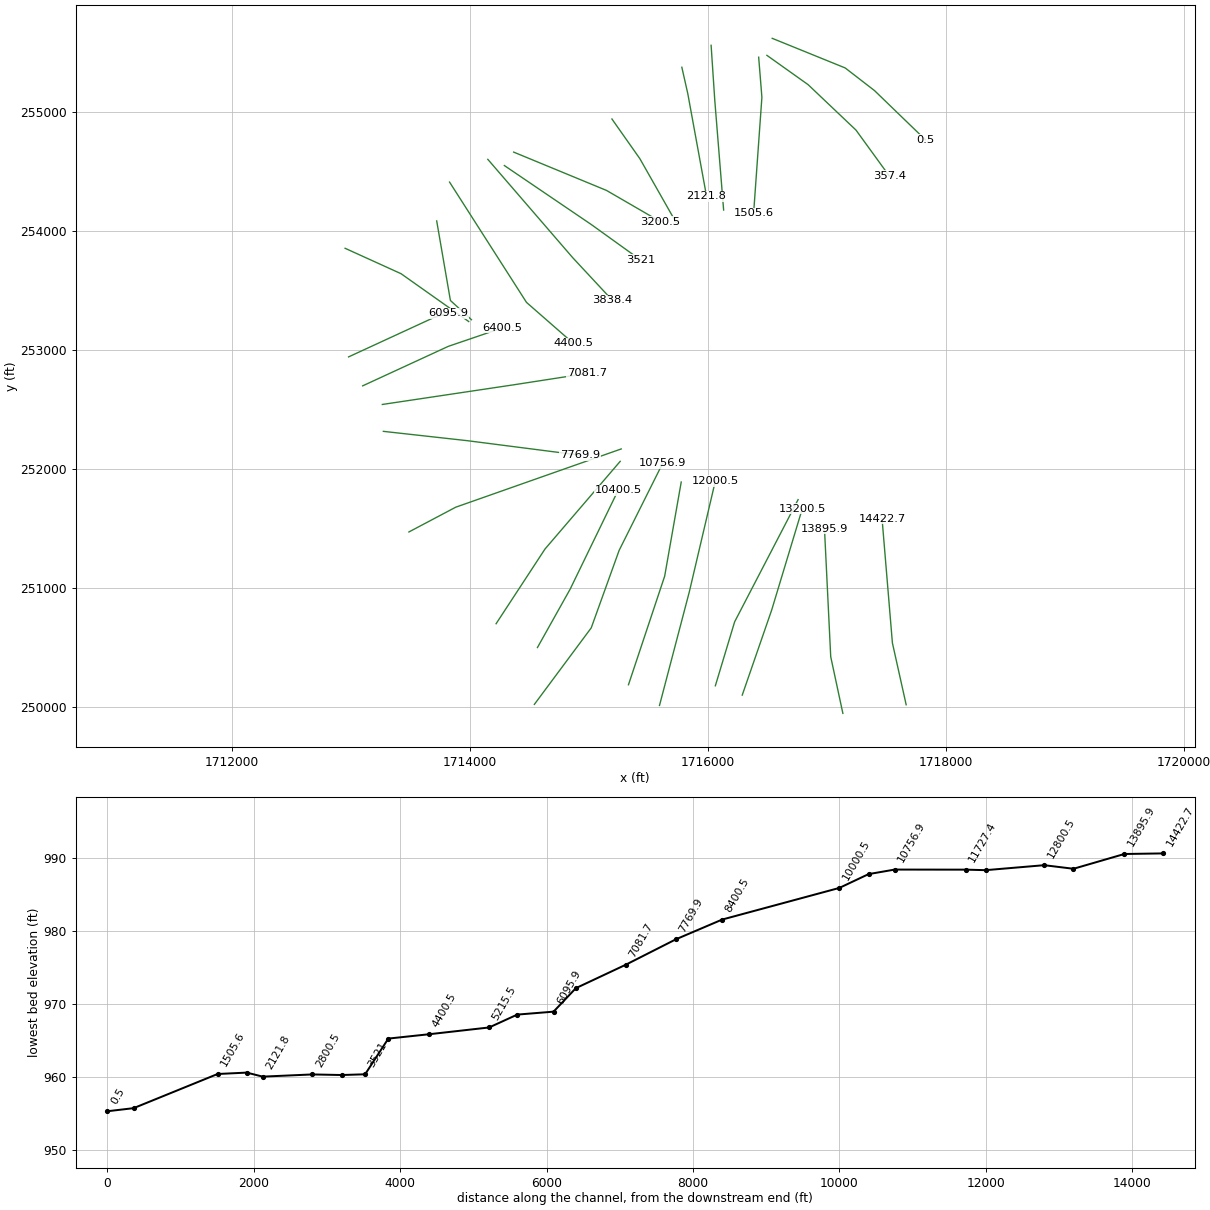
HEC-RAS study LostCrLR.prj: LostCrLR

--- LostCrLR.g01 (geometry) --- (continued)

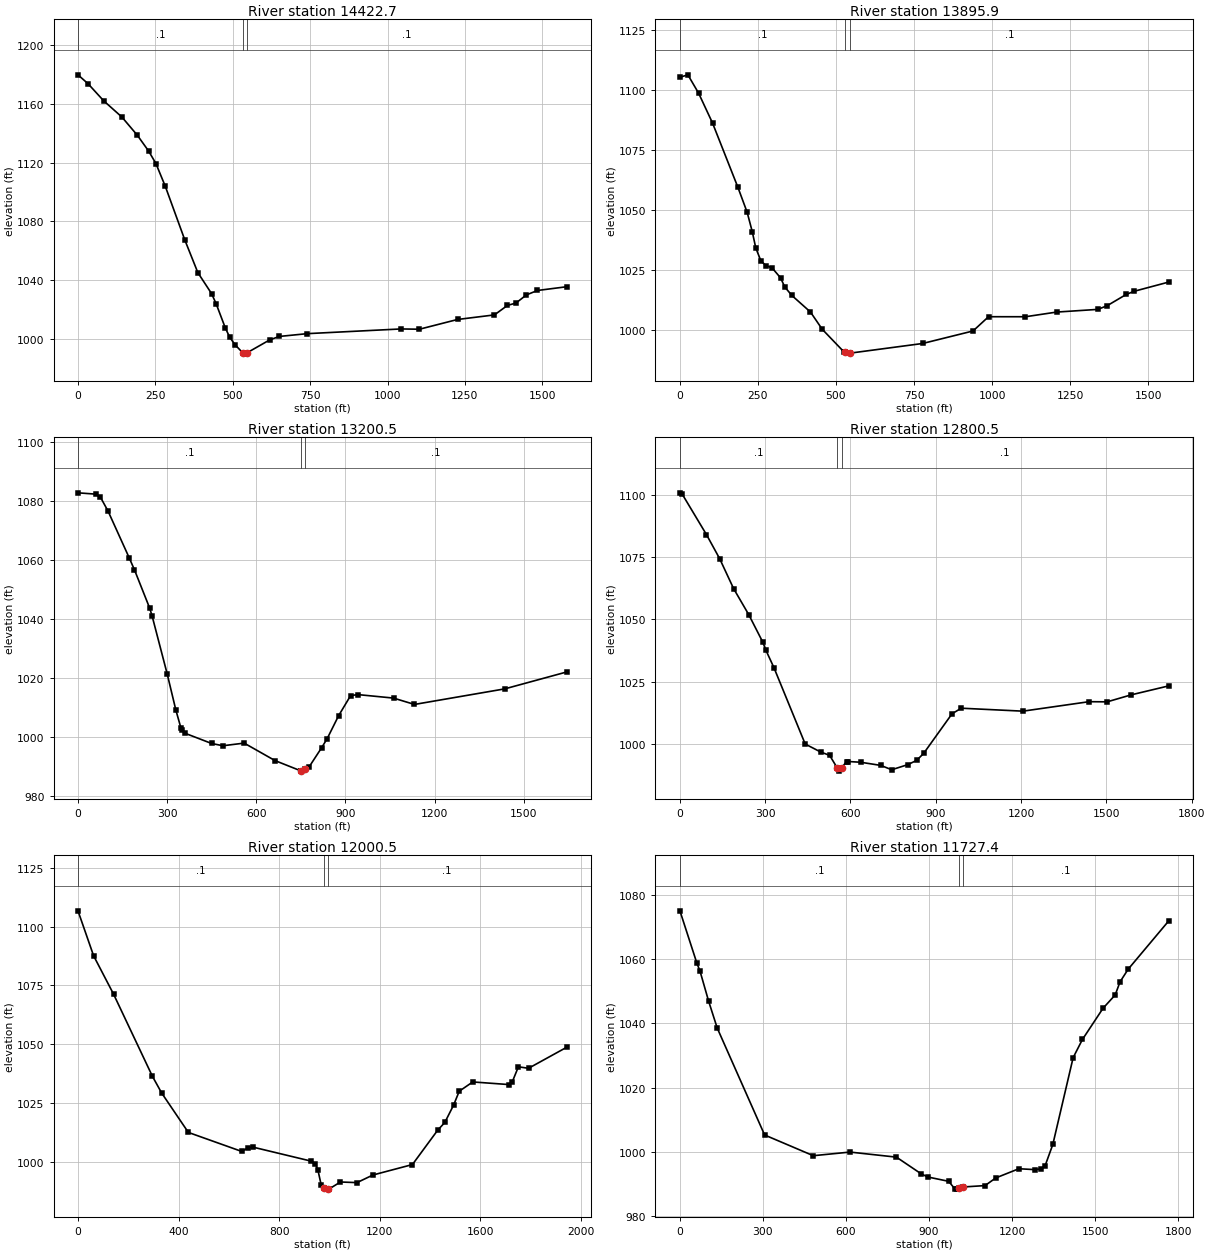
Type RM Length L Ch R = 1 ,14422.7,529.674,526.787,526.01
XS GIS Cut Line= 3
     1717667.597      250021.930     1717551.906      250541.055
     1717465.013      251584.042
#Sta/Elev= 30
       0 1179.56    32.6 1173.51    83.0 1161.93   141.9 1150.89   191.7 1138.55
   228.5 1127.73   251.9 1119.27   282.2 1103.81   345.1 1067.46   387.3 1045.24
   431.4 1031.07   446.1 1024.26   475.8 1007.79   490.1 1001.42   507.0  996.37
   531.6  990.98   543.2  990.60   546.6  990.88   619.3  999.58   650.4 1001.93
   741.1 1003.83  1043.6 1007.02  1103.1 1006.83  1226.1 1013.45  1345.3 1016.55
  1387.5 1023.01  1414.8 1024.59  1448.6 1030.13  1484.4 1033.14  1578.5 1035.67
#Mann= 3 , 0 , 0
       0     0.1       0   531.6   0.045       0   546.6     0.1       0
Bank Sta=   531.6,   546.6
Exp/Cntr=0.3,0.1

Type RM Length L Ch R = 1 ,13895.9,704.788,695.467,687.206
XS GIS Cut Line= 3
     1717135.554      249949.572     1717033.469      250425.798
     1716980.964      251503.051
#Sta/Elev= 30
       0 1105.31    25.5 1106.32    59.8 1098.71   104.6 1086.24   185.6 1059.58
   215.5 1049.09   231.7 1041.12   243.0 1034.32   259.5 1028.89   275.5 1026.97
   295.5 1025.97   322.3 1021.87   336.0 1018.05   358.8 1014.50   418.3 1007.62
   456.0 1000.45   524.5  991.18   530.5  990.95   542.2  990.52   545.5  990.52
   777.6  994.53   939.2  999.74   988.8 1005.67  1107.1 1005.66  1206.9 1007.60
  1338.8 1008.72  1368.6 1010.23  1429.9 1014.93  1455.5 1016.26  1565.6 1020.07
#Mann= 3 , 0 , 0
       0     0.1       0   530.5   0.045       0   545.5     0.1       0
Bank Sta=   530.5,   545.5
Exp/Cntr=0.3,0.1

Type RM Length L Ch R = 1 ,13200.5,398.1,400,395.906
XS GIS Cut Line= 3
     1716289.918      250103.271     1716537.513      250818.702
     1716794.061      251667.852
#Sta/Elev= 30
       0 1082.77    60.6 1082.32    75.5 1081.30   101.1 1076.60   172.0 1060.84
   190.1 1056.68   241.4 1043.68   249.6 1040.99   300.1 1021.46   329.2 1009.24
   346.2 1003.18   349.6 1002.60   361.7 1001.27   449.8  997.86   487.8  997.10
   559.2  997.99   663.0  992.07   749.6  988.60   751.6  988.50   764.6  989.10
   776.5  989.75   819.4  996.36   838.5  999.51   877.1 1007.30   917.2 1014.06
   941.2 1014.43  1061.8 1013.24  1132.2 1011.09  1435.8 1016.36  1644.1 1022.08
#Mann= 3 , 0 , 0
       0     0.1       0   749.6   0.045       0   764.6     0.1       0
Bank Sta=   749.6,   764.6
Exp/Cntr=0.3,0.1

Type RM Length L Ch R = 1 ,12800.5,798.358,800,807.026
XS GIS Cut Line= 3
     1716063.923      250181.500     1716225.766      250718.605
     1716759.293      251746.081
#Sta/Elev= 30
       0 1100.93     7.1 1100.59    93.4 1084.13   139.8 1074.45   188.7 1062.44
   242.2 1051.92   291.9 1040.78   301.8 1037.78   330.7 1030.62   440.7  999.89
   494.6  996.71   526.7  995.32   553.5  990.24   559.5  988.99   568.5  990.29
   586.0  992.82   591.8  992.86   636.0  992.56   706.6  991.29   745.0  989.54
   801.7  991.61   832.8  993.31   857.5  996.15   957.1 1012.05   989.5 1014.30
  1206.4 1013.11  1439.1 1016.92  1502.7 1016.86  1587.6 1019.68  1718.7 1023.26
#Mann= 3 , 0 , 0
       0     0.1       0   553.5   0.045       0   568.5     0.1       0
Bank Sta=   553.5,   568.5
Exp/Cntr=0.3,0.1

Type RM Length L Ch R = 1 ,12000.5,270.204,273.099,275.1
XS GIS Cut Line= 3
     1715594.549      250016.349     1715844.903      250970.152
     1716063.923      251902.539
#Sta/Elev= 30
       0 1106.78    62.2 1087.64   141.8 1071.27   296.4 1036.28   333.2 1029.18
   439.1 1012.45   651.6 1004.35   676.9 1005.96   698.0 1006.14   925.2 1000.29
   944.7  999.10   954.4  996.50   967.4  990.19   978.6  988.62   993.6  988.35
   998.1  988.31  1044.2  991.35  1109.9  991.08  1173.3  994.32  1330.5  998.77
  1431.1 1013.41  1459.4 1016.69  1494.3 1024.08  1516.8 1029.99  1570.5 1033.94
  1715.6 1032.81  1727.7 1033.98  1752.1 1040.38  1792.4 1039.75  1943.9 1048.68
#Mann= 3 , 0 , 0
       0     0.1       0   978.6   0.045       0   993.6     0.1       0
Bank Sta=   978.6,   993.6
Exp/Cntr=0.3,0.1

Type RM Length L Ch R = 1 ,11727.4,977.698,970.476,963.305
XS GIS Cut Line= 3
     1715333.785      250190.192     1715638.010      251102.864
     1715777.084      251893.847
#Sta/Elev= 30
       0 1075.05    61.1 1058.80    73.0 1056.16   103.8 1046.89   134.7 1038.56
   306.0 1005.24   481.9  998.79   614.6  999.92   782.2  998.34   870.6  993.20
   894.9  992.17   971.0  990.81   992.7  988.51  1002.1  988.38    1008  988.66
    1023  989.05  1102.3  989.48  1140.9  991.86  1224.4  994.73  1283.0  994.45
  1304.0  994.70  1319.3  995.67  1347.2 1002.31  1420.5 1029.32  1454.0 1034.98
  1528.6 1044.71  1572.4 1048.85  1590.0 1052.94  1619.4 1056.88  1765.2 1071.85
#Mann= 3 , 0 , 0
       0     0.1       0    1008   0.045       0    1023     0.1       0
Bank Sta=    1008,    1023
Exp/Cntr=0.3,0.1

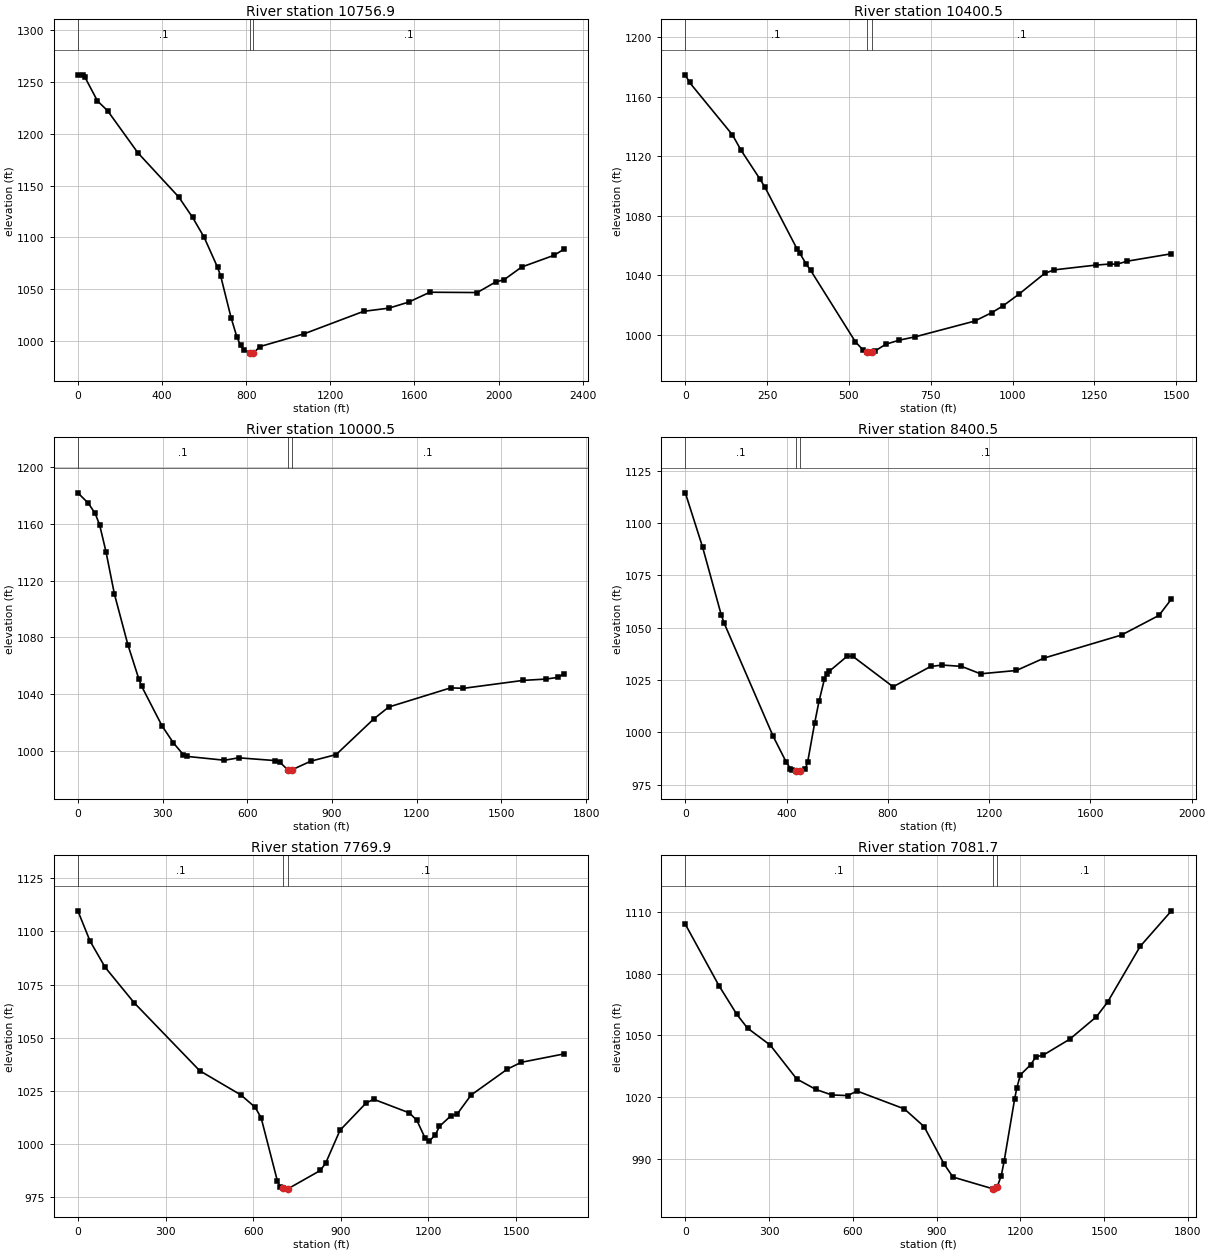
Type RM Length L Ch R = 1 ,10756.9,359.427,356.425,355.089
XS GIS Cut Line= 4
     1714542.803      250025.041     1715020.869      250668.258
     1715255.556      251320.167     1715620.625      252050.305
#Sta/Elev= 30
       0 1256.44    23.2 1256.93    34.1 1254.48    93.1 1231.78   142.1 1222.11
   285.7 1181.60   480.0 1138.92   545.5 1119.30   600.1 1100.25   664.2 1071.15
   679.0 1062.78   728.4 1022.53   755.4 1004.40   773.4  995.77   790.2  990.99
   817.6  988.84   832.6  988.41   834.6  988.39   864.6  994.64  1075.8 1007.06
  1358.3 1028.71  1478.8 1031.81  1573.0 1037.66  1673.1 1047.15  1898.6 1046.84
  1986.4 1057.11  2025.7 1059.16  2109.3 1071.44  2264.3 1082.85  2310.6 1088.63
#Mann= 3 , 0 , 0
       0     0.1       0   817.6   0.045       0   832.6     0.1       0
Bank Sta=   817.6,   832.6
Exp/Cntr=0.3,0.1

Type RM Length L Ch R = 1 ,10400.5,402.166,400,392.829
XS GIS Cut Line= 3
     1714568.879      250503.108     1714843.886      250994.147
     1715246.864      251824.310
#Sta/Elev= 30
       0 1174.74    13.0 1169.59   144.0 1134.41   170.5 1124.03   228.9 1104.45
   243.6 1099.14   342.2 1057.44   350.0 1054.92   369.4 1047.53   382.7 1043.48
   519.6  995.44   544.3  989.61   555.3  988.51   562.8  987.77   570.3  988.60
   580.8  989.32   612.5  993.74   654.2  996.51   701.3  998.66   884.4 1009.30
   936.1 1014.93   970.3 1019.41  1020.1 1027.47  1098.2 1041.34  1127.5 1043.71
  1253.8 1046.90  1299.4 1047.66  1318.3 1047.45  1349.9 1049.51  1485.6 1054.53
#Mann= 3 , 0 , 0
       0     0.1       0   555.3   0.045       0   570.3     0.1       0
Bank Sta=   555.3,   570.3
Exp/Cntr=0.3,0.1

Type RM Length L Ch R = 1 ,10000.5,1612.483,1600,1586.763
XS GIS Cut Line= 3
     1714221.195      250703.027     1714632.313      251330.963
     1715264.249      252067.689
#Sta/Elev= 30
       0 1181.77    36.6 1174.53    61.2 1167.33    77.2 1159.13    99.5 1140.45
   129.6 1110.41   177.1 1074.89   216.2 1050.56   226.2 1045.49   298.0 1017.76
   338.4 1005.74   373.4  997.47   387.6  996.22   519.2  993.55   569.5  995.25
   698.6  993.31   714.8  992.27     743  986.84   750.5  985.88     758  986.79
   824.6  992.88   914.6  997.53  1047.4 1022.54  1100.9 1031.00  1320.2 1044.49
  1365.3 1044.16  1576.3 1049.74  1658.0 1050.68  1699.9 1051.87  1721.2 1054.37
#Mann= 3 , 0 , 0
       0     0.1       0     743   0.045       0     758     0.1       0
Bank Sta=     743,     758
Exp/Cntr=0.3,0.1

Type RM Length L Ch R = 1 ,8400.5,641.817,630.544,622.735
XS GIS Cut Line= 3
     1713488.484      251474.215     1713881.781      251682.258
     1715272.941      252171.994
#Sta/Elev= 30
       0 1114.39    68.0 1088.57   141.5 1056.31   153.1 1052.27   347.3  998.09
   398.9  985.79   415.3  982.77   420.1  981.90   437.4  981.72   452.4  981.57
   453.5  981.56   473.7  982.48   483.2  985.93   510.8 1004.51   528.2 1015.01
   549.1 1025.35   557.6 1027.82   569.1 1029.28   639.6 1036.45   661.0 1036.40
   820.6 1021.82   968.9 1031.52  1014.8 1032.18  1090.7 1031.57  1165.9 1028.01
  1307.3 1029.59  1417.6 1035.55  1722.7 1046.52  1870.7 1055.89  1919.8 1063.69
#Mann= 3 , 0 , 0
       0     0.1       0   437.4   0.045       0   452.4     0.1       0
Bank Sta=   437.4,   452.4
Exp/Cntr=0.3,0.1

Type RM Length L Ch R = 1 ,7769.9,684.532,688.199,692.467
XS GIS Cut Line= 3
     1713273.754      252319.760     1713977.815      252241.531
     1714925.256      252119.842
#Sta/Elev= 30
       0 1109.64    41.7 1095.44    93.5 1083.09   192.5 1066.47   417.2 1034.49
   558.0 1023.12   606.6 1017.36   627.2 1012.42   682.8  982.74   693.4  979.67
   703.6  979.23   717.0  978.87   718.6  978.99   830.0  987.65   848.5  991.20
   897.3 1006.55   987.1 1019.42  1012.9 1021.08  1135.0 1014.66  1160.4 1011.15
  1187.9 1002.99  1201.8 1001.37  1223.4 1004.30  1237.3 1008.34  1275.5 1013.18
  1297.2 1013.96  1345.6 1023.05  1470.0 1035.26  1517.4 1038.45  1663.6 1042.40
#Mann= 3 , 0 , 0
       0     0.1       0   703.6   0.045       0   718.6     0.1       0
Bank Sta=   703.6,   718.6
Exp/Cntr=0.3,0.1

Type RM Length L Ch R = 1 ,7081.7,676.743,681.258,680.564
XS GIS Cut Line= 3
     1713265.062      252545.755     1714368.961      252710.906
     1714986.101      252806.519
#Sta/Elev= 30
       0 1103.94   120.7 1074.08   184.5 1060.19   222.7 1053.53   304.1 1045.28
   398.8 1028.86   467.5 1023.77   524.6 1021.09   581.7 1020.78   614.9 1023.00
   784.3 1014.32   855.0 1005.74   927.0  987.48   958.4  981.24  1102.2  975.50
  1107.1  975.38  1117.2  976.64  1131.1  981.76  1141.5  988.82  1179.2 1019.07
  1186.9 1024.40  1199.6 1030.80  1237.1 1035.82  1255.1 1039.58  1281.6 1040.42
  1376.4 1048.14  1472.3 1059.07  1511.9 1066.11  1628.7 1093.19  1740.7 1110.46
#Mann= 3 , 0 , 0
       0     0.1       0  1102.2   0.045       0  1117.2     0.1       0
Bank Sta=  1102.2,  1117.2
Exp/Cntr=0.3,0.1

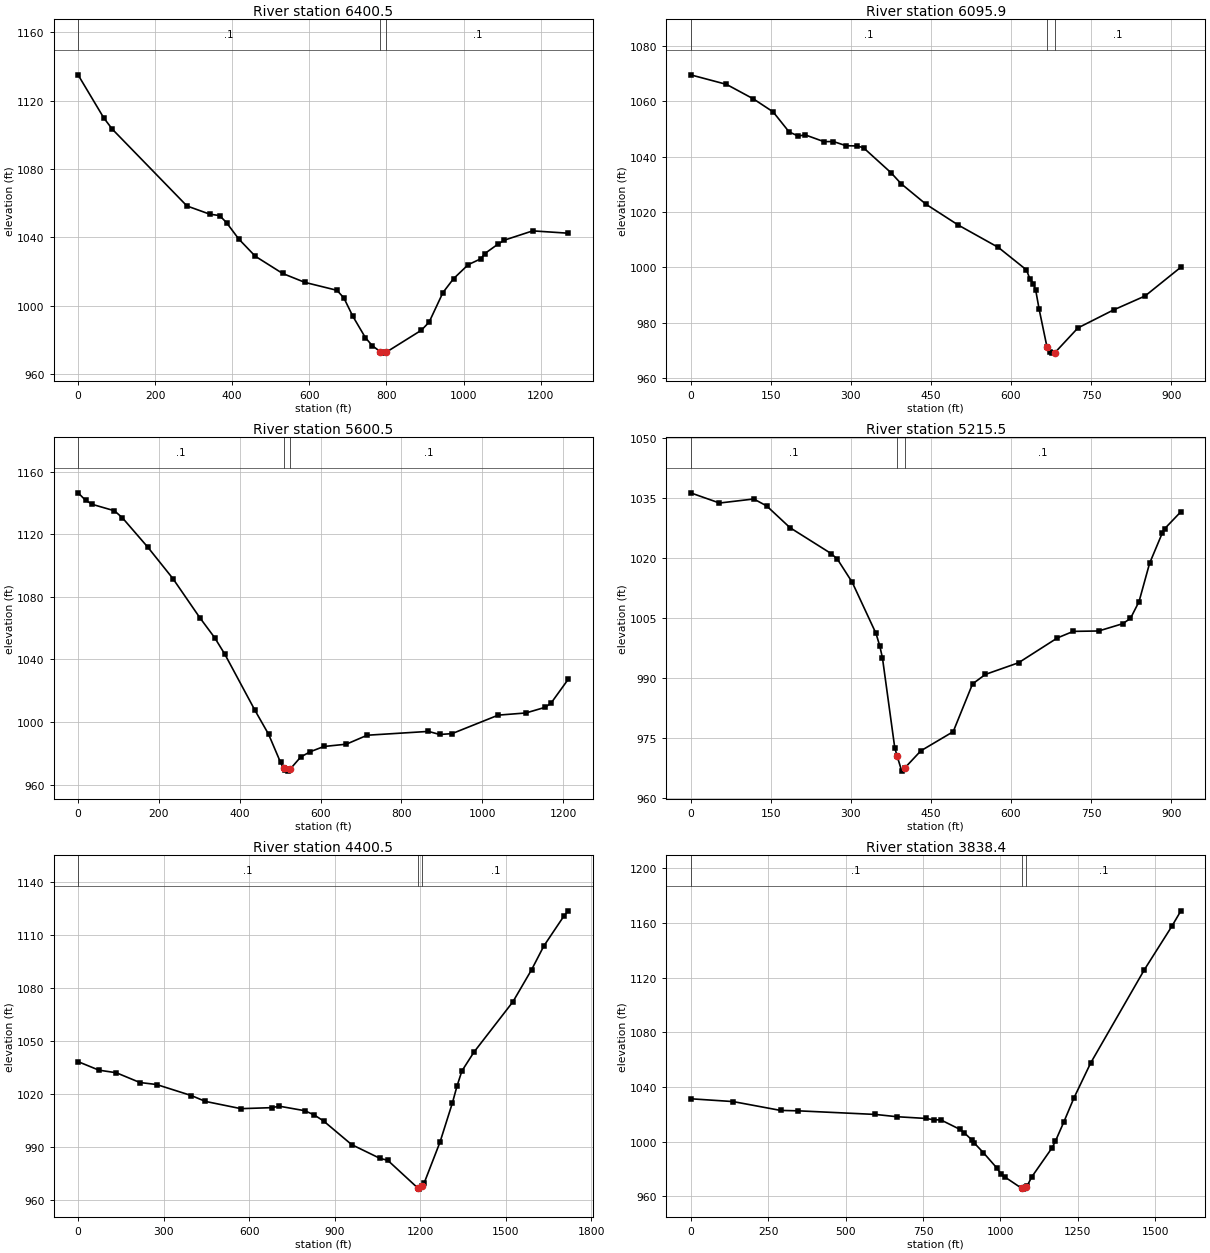
Type RM Length L Ch R = 1 ,6400.5,302.672,304.589,311.631
XS GIS Cut Line= 3
     1713099.911      252702.214     1713819.011      253033.871
     1714273.347      253188.972
#Sta/Elev= 30
       0 1135.06    66.7 1109.85    88.9 1103.24   282.5 1058.31   341.6 1053.51
   367.3 1052.68   385.2 1048.54   416.7 1039.03   459.7 1028.90   530.7 1018.81
   588.5 1013.58   671.6 1008.95   689.5 1004.53   712.7  993.82   745.3  981.29
   763.2  976.55   784.4  972.99   795.9  972.18   799.4  972.71   890.6  985.57
   910.8  990.33   946.7 1007.65   974.2 1015.76  1012.2 1023.95  1045.3 1027.43
  1055.1 1030.42  1088.5 1035.82  1105.7 1038.28  1179.5 1043.73  1272.0 1042.36
#Mann= 3 , 0 , 0
       0     0.1       0   784.4   0.045       0   799.4     0.1       0
Bank Sta=   784.4,   799.4
Exp/Cntr=0.3,0.1

Type RM Length L Ch R = 1 ,6095.9,514.874,495.411,471.637
XS GIS Cut Line= 3
     1712981.532      252945.492     1713700.632      253277.149
     1713821.936      253311.870
#Sta/Elev= 30
       0 1069.55    67.2 1066.10   117.5 1060.86   154.5 1056.16   184.4 1048.93
   201.6 1047.41   214.3 1047.87   249.7 1045.40   267.4 1045.44   291.1 1043.93
   312.4 1043.84   324.1 1043.13   375.3 1034.17   394.2 1030.20   441.0 1022.75
   501.5 1015.22   576.4 1007.16   628.9  999.05   635.3  995.80   642.0  994.05
   646.2  991.74   652.7  984.77   667.3  971.24   672.7  969.20   675.9  968.97
   682.3  969.17   725.3  978.08   791.9  984.57   851.0  989.62   918.1 1000.04
#Mann= 3 , 0 , 0
       0     0.1       0   667.3   0.045       0   682.3     0.1       0
Bank Sta=   667.3,   682.3
Exp/Cntr=0.3,0.1

Type RM Length L Ch R = 1 ,5600.5,407.054,384.922,367.102
XS GIS Cut Line= 3
     1712952.145      253858.265     1713422.451      253644.702
     1713991.061      253242.683
#Sta/Elev= 30
       0 1146.59    18.6 1141.85    35.1 1139.22    90.0 1135.11   109.8 1130.58
   172.6 1111.80   234.6 1091.75   301.4 1066.65   338.0 1053.91   363.1 1043.35
   437.8 1007.38   471.4  992.11   501.0  974.09     509  970.32   511.3  969.29
   520.1  968.57     524  969.64   550.7  977.57   574.1  980.95   608.1  984.33
   663.6  985.80   715.2  991.53   866.9  993.98   894.6  992.01   925.1  992.55
  1039.4 1004.38  1107.9 1005.78  1155.8 1009.41  1170.3 1012.15  1212.9 1027.42
#Mann= 3 , 0 , 0
       0     0.1       0     509   0.045       0     524     0.1       0
Bank Sta=     509,     524
Exp/Cntr=0.3,0.1

Type RM Length L Ch R = 1 ,5215.5,806.043,815.078,831.794
XS GIS Cut Line= 3
     1713721.999      254088.305     1713837.311      253419.495
     1714014.233      253257.990
#Sta/Elev= 30
       0 1036.41    54.1 1033.86   118.3 1034.87   142.4 1033.14   186.1 1027.70
   263.3 1021.21   275.0 1019.80   302.7 1014.03   347.2 1001.24   354.3  998.09
   359.3  995.12   382.3  972.68   386.8  970.56   395.4  966.81   401.8  967.70
   431.1  971.88   491.8  976.68   528.0  988.62   552.1  991.00   614.1  993.91
   687.0 1000.13   716.6 1001.76   764.2 1001.86   809.0 1003.67   823.7 1004.99
   839.8 1009.21   859.5 1018.76   883.3 1026.34   888.0 1027.47   918.2 1031.68
#Mann= 3 , 0 , 0
       0     0.1       0   386.8   0.045       0   401.8     0.1       0
Bank Sta=   386.8,   401.8
Exp/Cntr=0.3,0.1

Type RM Length L Ch R = 1 ,4400.5,558.979,562.062,557.736
XS GIS Cut Line= 3
     1713830.049      254414.561     1714476.759      253403.534
     1714867.856      253061.625
#Sta/Elev= 30
       0 1038.15    73.4 1033.31   134.1 1031.86   216.8 1026.32   275.2 1025.19
   397.4 1018.92   446.7 1015.61   571.2 1011.50   679.9 1012.07   706.0 1012.89
   795.3 1010.33   828.5 1007.92   861.1 1004.51   959.4  991.14  1059.8  983.25
  1085.6  982.30  1192.7  966.35  1196.4  965.89  1207.7  967.80  1213.3  969.11
  1269.4  992.52  1313.1 1014.86  1329.1 1024.30  1346.2 1032.86  1388.5 1043.54
  1525.2 1072.09  1590.7 1090.26  1633.6 1103.70  1705.0 1120.91  1719.6 1123.63
#Mann= 3 , 0 , 0
       0     0.1       0  1192.7   0.045       0  1207.7     0.1       0
Bank Sta=  1192.7,  1207.7
Exp/Cntr=0.3,0.1

Type RM Length L Ch R = 1 ,3838.4,311.348,317.385,322.687
XS GIS Cut Line= 3
     1714151.658      254605.787     1714864.411      253780.036
     1715199.354      253420.229
#Sta/Elev= 30
       0 1031.39   137.1 1029.34   290.3 1022.87   347.2 1022.57   596.2 1019.93
   666.5 1018.25   759.2 1017.00   784.1 1016.03   807.5 1015.94   868.2 1009.12
   882.1 1006.71   908.5 1001.13   916.1  998.87   945.1  991.91   988.2  980.79
  1001.3  976.51  1013.7  974.23    1068  965.98  1072.9  965.29    1083  966.93
  1085.5  967.40  1101.8  974.47  1166.5  995.47  1177.2 1000.25  1204.4 1014.32
  1237.2 1032.00  1291.3 1057.61  1464.4 1125.77  1552.8 1157.44  1582.4 1168.88
#Mann= 3 , 0 , 0
       0     0.1       0    1068   0.045       0    1083     0.1       0
Bank Sta=    1068,    1083
Exp/Cntr=0.3,0.1

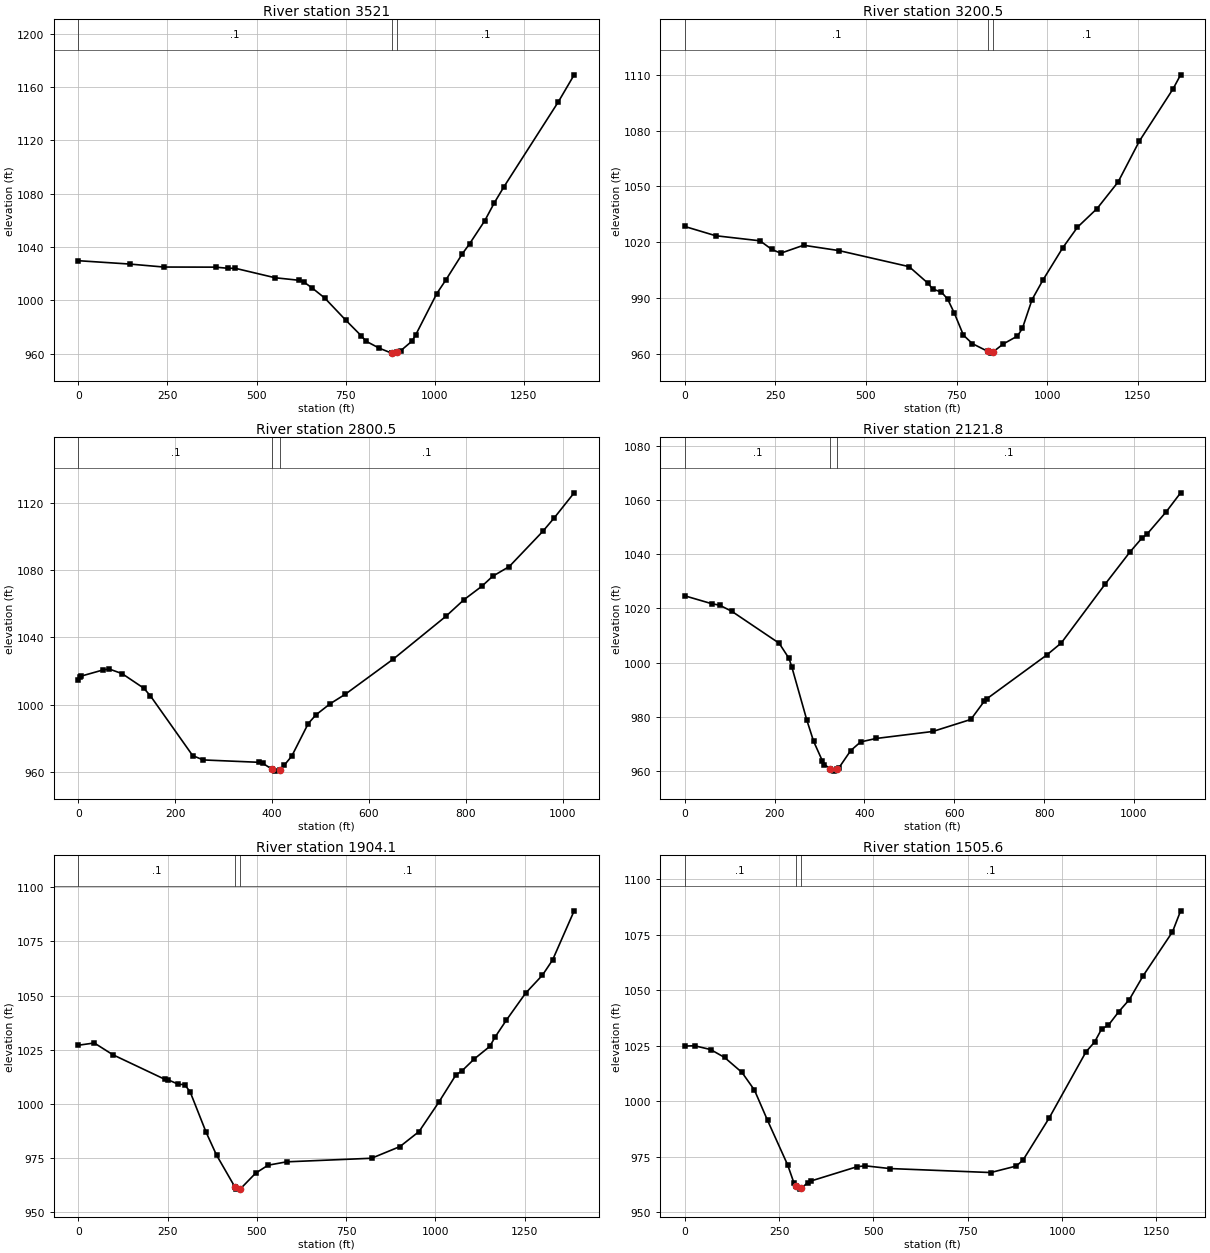
Type RM Length L Ch R = 1 ,3521,315.749,320.553,322.732
XS GIS Cut Line= 3
     1714290.731      254553.634     1715020.869      254058.184
     1715434.032      253761.200
#Sta/Elev= 30
       0 1029.72   143.9 1027.21   239.7 1024.97   385.0 1024.89   420.5 1024.02
   440.1 1024.04   552.2 1016.93   619.0 1015.05   632.8 1013.74   656.6 1009.14
   691.1 1001.80   750.6  985.06   794.1  973.33   807.1  969.38   844.5  964.10
   879.1  960.41   880.3  960.48   895.3  961.48   904.2  962.14   935.9  969.35
   946.6  974.09  1005.8 1005.09  1031.5 1015.42  1077.3 1034.83  1097.7 1042.37
  1140.3 1059.67  1167.4 1073.24  1194.3 1085.20  1347.0 1148.93  1391.2 1169.11
#Mann= 3 , 0 , 0
       0     0.1       0   880.3   0.045       0   895.3     0.1       0
Bank Sta=   880.3,   895.3
Exp/Cntr=0.3,0.1

Type RM Length L Ch R = 1 ,3200.5,413.308,400,387.101
XS GIS Cut Line= 3
     1714368.961      254666.632     1715148.988      254344.607
     1715602.629      254081.673
#Sta/Elev= 30
       0 1028.44    85.3 1023.46   207.6 1020.73   240.1 1016.08   264.9 1014.07
   327.7 1018.34   425.3 1015.47   619.0 1006.83   671.8  997.77   683.9  994.77
   708.1  993.16   725.3  989.36   743.4  982.00   768.8  970.00   793.3  965.44
   836.4  961.23   845.6  960.31   851.4  961.08   878.8  965.24   917.9  969.50
   931.6  973.63   958.2  989.10   988.6  999.73  1043.2 1017.06  1083.6 1028.05
  1137.7 1038.09  1195.7 1052.39  1254.2 1074.32  1347.3 1102.45  1368.2 1110.02
#Mann= 3 , 0 , 0
       0     0.1       0   836.4   0.045       0   851.4     0.1       0
Bank Sta=   836.4,   851.4
Exp/Cntr=0.3,0.1

Type RM Length L Ch R = 1 ,2800.5,688.412,678.673,671.611
XS GIS Cut Line= 3
     1715194.712      254944.780     1715429.658      254611.022
     1715733.623      254075.568
#Sta/Elev= 30
       0 1014.54     3.3 1016.62     5.6 1016.96    50.2 1020.59    63.5 1021.23
    90.3 1018.47   135.2 1009.78   148.9 1005.20   236.1  969.64   257.8  967.06
   373.4  965.64   380.5  965.11   400.7  961.42   406.1  960.39   415.7  961.14
   425.3  963.94   440.8  969.37   474.8  988.74   490.8  993.94   520.3 1000.58
   551.1 1006.15   650.4 1027.12   759.0 1052.60   796.4 1062.50   833.5 1070.56
   855.6 1076.45   889.9 1082.24   959.0 1103.15   982.9 1111.28  1023.9 1126.15
#Mann= 3 , 0 , 0
       0     0.1       0   400.7   0.045       0   415.7     0.1       0
Bank Sta=   400.7,   415.7
Exp/Cntr=0.3,0.1

Type RM Length L Ch R = 1 ,2121.8,220.111,217.691,215.367
XS GIS Cut Line= 3
     1715782.240      255379.799     1715832.293      255157.773
     1715989.801      254295.866
#Sta/Elev= 30
       0 1024.66    60.2 1021.75    77.5 1021.22   104.7 1018.95   210.0 1007.21
   232.0 1001.61   238.5  998.31   271.9  978.75   286.7  971.09   306.1  963.93
   310.9  962.45     324  960.98   331.5  960.09     339  960.84   342.6  961.19
   369.3  967.65   391.4  970.84   425.5  972.11   552.1  974.70   636.8  979.13
   667.0  985.91   673.0  986.81   805.7 1002.85   838.1 1007.29   935.2 1028.85
   991.3 1040.87  1017.0 1045.80  1029.5 1047.48  1071.3 1055.53  1103.8 1062.60
#Mann= 3 , 0 , 0
       0     0.1       0     324   0.045       0     339     0.1       0
Bank Sta=     324,     339
Exp/Cntr=0.3,0.1

Type RM Length L Ch R = 1 ,1904.1,398.141,398.529,399.057
XS GIS Cut Line= 3
     1716028.239      255564.298     1716058.989      255103.050
     1716133.460      254179.873
#Sta/Elev= 30
       0 1027.09    44.7 1028.13    96.4 1022.73   241.4 1011.41   250.6 1011.18
   279.6 1009.10   298.1 1008.86   313.2 1005.51   357.9  986.86   387.0  976.36
   438.8  961.52   441.9  960.64   453.8  960.76   496.5  968.01   531.1  971.68
   583.0  973.24   821.1  974.90   900.6  980.29   954.1  987.24  1008.9 1000.66
  1057.5 1013.44  1074.2 1015.25  1109.0 1020.80  1152.0 1026.53  1167.0 1030.87
  1198.7 1038.71  1252.4 1051.13  1299.5 1059.43  1327.9 1066.43  1388.4 1089.16
#Mann= 3 , 0 , 0
       0     0.1       0   438.8   0.045       0   453.8     0.1       0
Bank Sta=   438.8,   453.8
Exp/Cntr=0.3,0.1

Type RM Length L Ch R = 1 ,1505.6,1131.704,1148.147,1164.354
XS GIS Cut Line= 3
     1716427.987      255464.361     1716455.069      255127.314
     1716385.532      254153.797
#Sta/Elev= 30
       0 1024.90    25.8 1025.04    68.2 1023.34   105.3 1019.78   151.6 1013.01
   184.6 1005.07   219.3  991.42   272.8  971.27   289.3  963.21   293.6  961.70
   306.4  960.45   308.6  960.78   325.7  963.38   335.6  964.18   457.0  970.57
   478.7  970.94   542.7  969.73   810.8  967.92   878.4  970.85   896.3  973.50
   965.3  992.37  1063.3 1022.29  1086.1 1026.72  1104.7 1032.57  1122.8 1034.33
  1150.0 1040.35  1178.2 1045.84  1215.1 1056.66  1292.5 1076.34  1314.1 1085.82
#Mann= 3 , 0 , 0
       0     0.1       0   293.6   0.045       0   308.6     0.1       0
Bank Sta=   293.6,   308.6
Exp/Cntr=0.3,0.1

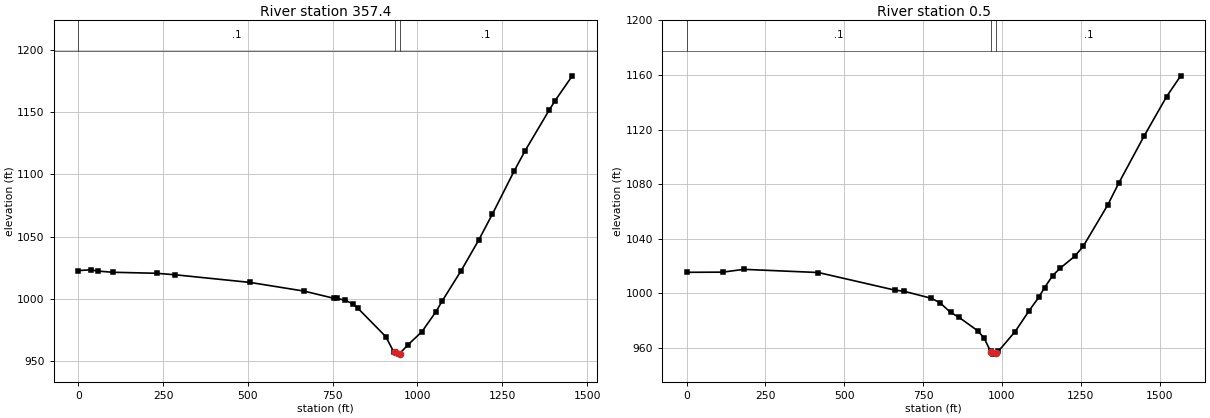
Type RM Length L Ch R = 1 ,357.4,354.707,356.96,356.568
XS GIS Cut Line= 4
     1716497.174      255479.736     1716843.110      255233.737
     1717245.884      254851.533     1717525.859      254465.709
#Sta/Elev= 30
       0 1022.79    36.7 1023.36    57.1 1022.38   101.6 1021.41   230.9 1020.60
   285.4 1019.41   506.1 1013.28   665.9 1006.30   755.3 1000.42   761.7 1000.41
   786.9  999.06   811.1  995.77   824.8  992.43   906.6  969.78   929.6  957.80
   932.5  957.44   945.8  955.78   947.5  956.16   970.6  962.88  1013.5  973.90
  1053.9  989.61  1073.7  998.74  1128.6 1022.67  1180.4 1047.17  1221.0 1068.15
  1284.7 1102.46  1317.5 1118.98  1388.1 1151.35  1405.8 1159.10  1456.4 1178.91
#Mann= 3 , 0 , 0
       0     0.1       0   932.5   0.045       0   947.5     0.1       0
Bank Sta=   932.5,   947.5
Exp/Cntr=0.3,0.1

Type RM Length L Ch R = 1 ,0.5,0,0.457,7.325
XS GIS Cut Line= 4
     1716541.990      255622.765     1717154.956      255373.982
     1717401.929      255183.222     1717828.423      254770.937
#Sta/Elev= 30
       0 1015.34   113.9 1015.46   181.7 1017.51   417.8 1015.18   659.6 1002.32
   690.6 1001.39   776.0  996.28   802.9  993.12   836.9  985.97   863.3  982.42
   922.8  972.52   943.3  967.20   963.7  957.38   966.1  956.73   972.1  955.36
   981.1  956.42   988.1  957.36  1041.8  971.91  1085.6  987.00  1117.2  997.22
  1135.1 1004.16  1160.9 1012.94  1183.8 1018.24  1230.6 1027.07  1257.6 1034.41
  1335.3 1064.65  1370.7 1080.92  1450.1 1114.98  1522.2 1144.21  1566.8 1159.38
#Mann= 3 , 0 , 0
       0     0.1       0   966.1   0.045       0   981.1     0.1       0
Bank Sta=   966.1,   981.1
Exp/Cntr=0.3,0.1